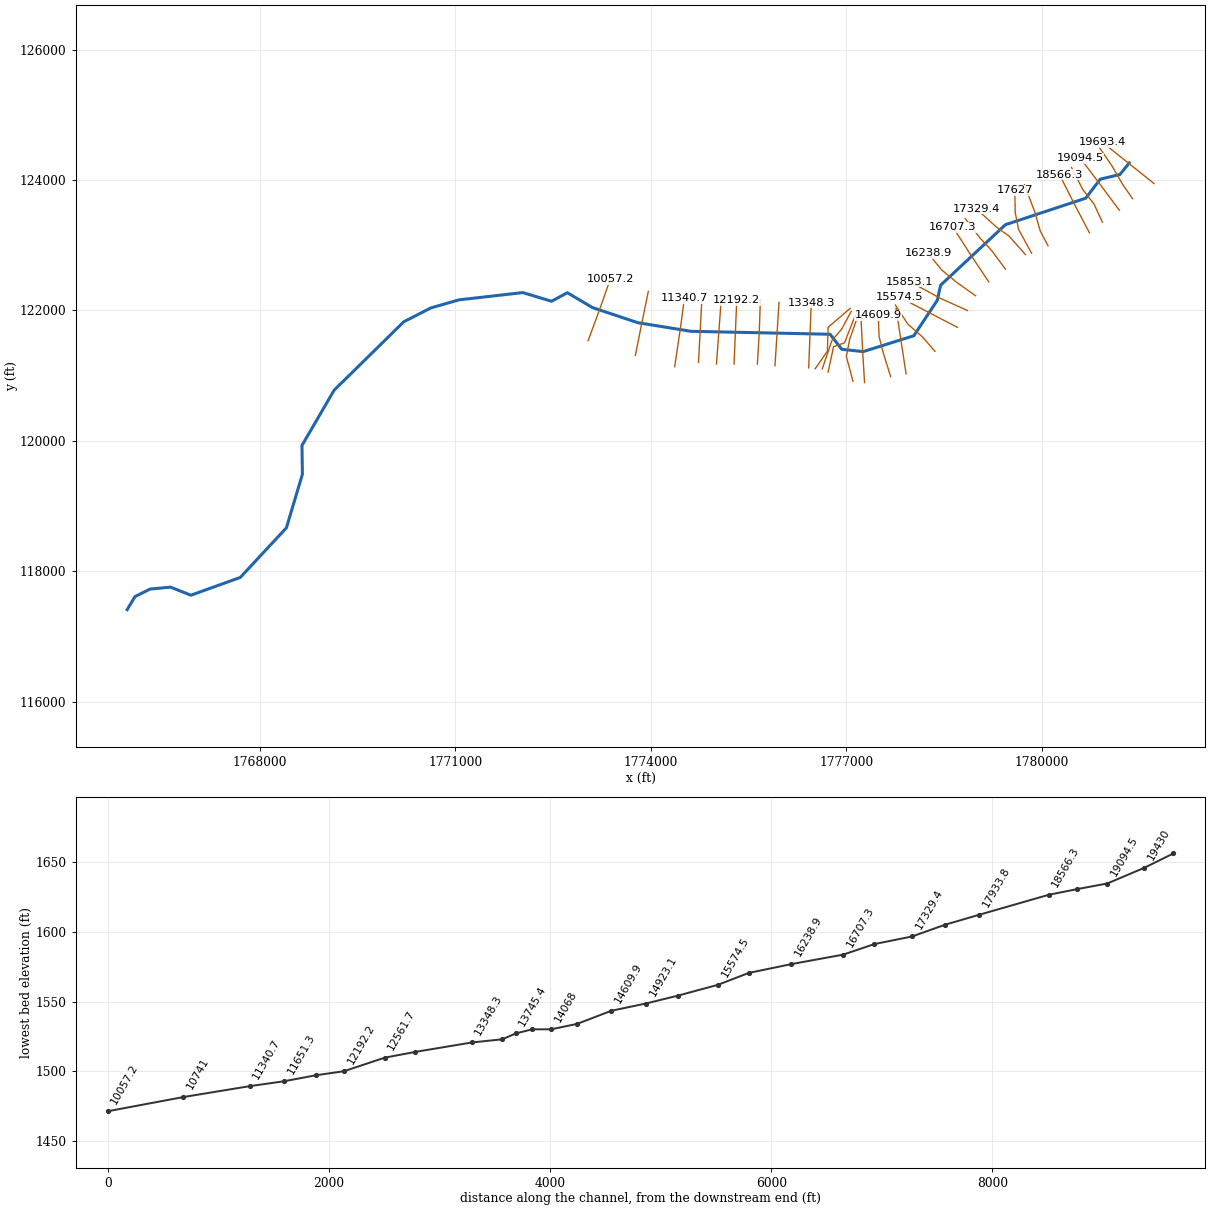
--- Barrenshe Creek.prj (project) ---

Proj Title=Barrenshe Creek
Current Plan=p01
Default Exp/Contr=0,0
English Units
Geom File=g01
Flow File=f01
Plan File=p01
BEGIN DESCRIPTION:
END DESCRIPTION:
DSS Export Rating Curves= 0
DSS Export Rating Curve Sorted= 0
DSS Export Volume Flow Curves= 0
DXF OffsetX= 0
DXF OffsetY= 0
DXF ScaleX= 0
DXF ScaleY= 0

--- Barrenshe Creek.p01 (plan) ---

Plan Title=Floodplain
Program Version=4.00
Geom File=g01
Flow File=f01
K Sum by GR=0
Std Step Tol=0.01
Critical Tol=0.01
Num of Std Step Trials=20
Max Error Tol=0.3
Flow Tol Ratio=0.001
Split Flow NTrial=30
Split Flow Tol=0.02
Split Flow Ratio=0.02
Log Output Level=0
Friction Slope Method=1
Unsteady Friction Slope Method=2
Unsteady Bridges Friction Slope Method=1
Global Log Level=0
CheckData=False
Run HTab=0
Run UNet=0
Run PostProcess=0
UNET Theta=0
UNET Theta Warmup=0
UNET ZTol=0
UNET ZSATol=0
UNET MxIter=0
UNET MaxInSteps=0
UNET DtIC=0
UNET DtMin=0
UNET MaxCRTS=0
UNET WFStab=0
UNET SFStab=0
UNET WFX=0
UNET SFX=0
UNET DSS MLevel=0
UNET DZMax Abort=0
UNET Convert EG Bridges=0
UNET Use Existing IB Tables=0
UNET Froude Limit=0
UNET Froude Power=0
Write IC File=0
Echo Input=False
Echo Output=False
Write Detailed=0

--- Barrenshe Creek.f01 (steady flow) ---

Flow Title=NFF Regression Equation
Program Version=4.00
Number of Profiles=1
Profile Names=P100yr
River Rch & RM=Barrenshe Creek,Main      ,19693.4
626.1812
River Rch & RM=Barrenshe Creek,Main      ,17933.8
660.3924
River Rch & RM=Barrenshe Creek,Main      ,17627
774.4855
River Rch & RM=Barrenshe Creek,Main      ,17329.4
834.8209
River Rch & RM=Barrenshe Creek,Main      ,15214.8
885.0308
River Rch & RM=Barrenshe Creek,Main      ,14923.1
1024.913
River Rch & RM=Barrenshe Creek,Main      ,12839.3
1092.986
River Rch & RM=Barrenshe Creek,Main      ,12561.7
1262.231
River Rch & RM=Barrenshe Creek,Main      ,12192.2
1272.774
River Rch & RM=Barrenshe Creek,Main      ,9567.7
1407.818
River Rch & RM=Barrenshe Creek,Main      ,9269.1
1750.220
River Rch & RM=Barrenshe Creek,Main      ,6569.3
1816.530
River Rch & RM=Barrenshe Creek,Main      ,6259.7
2243.922
River Rch & RM=Barrenshe Creek,Main      ,285
2456.917
Boundary for River Rch & Prof#=Barrenshe Creek,Main      ,1
Up Type=0
Dn Type=3
Dn Slope=0.022494

--- Barrenshe Creek.g01 (geometry) ---

Geom Title=USGS 10m DEM
Program Version=4.00

River Reach=Barrenshe Creek ,Main
Reach XY= 30
     1781337.093      124261.178     1781192.446      124082.809
      1780892.28      124012.578     1780669.953      123720.634
     1779437.953      123314.151     1778443.915      122385.909
     1778393.842      122155.704     1778033.181      121610.792
     1777255.727      121367.348     1776927.719      121403.112
     1776748.987      121633.643       1774615.3       121679.09
     1773800.684      121811.024     1773106.353      122041.864
     1772718.903      122270.893     1772475.961      122139.854
      1772036.86      122272.821     1771054.139      122160.881
     1770627.407      122037.809     1770211.807      121826.299
     1769142.442      120776.027     1768648.978      119928.269
     1768655.917      119486.913     1768409.996      118664.508
     1767703.694      117904.348     1766945.227      117631.177
     1766632.663      117755.504     1766319.605      117725.573
     1766089.059      117610.704     1765967.625      117409.851

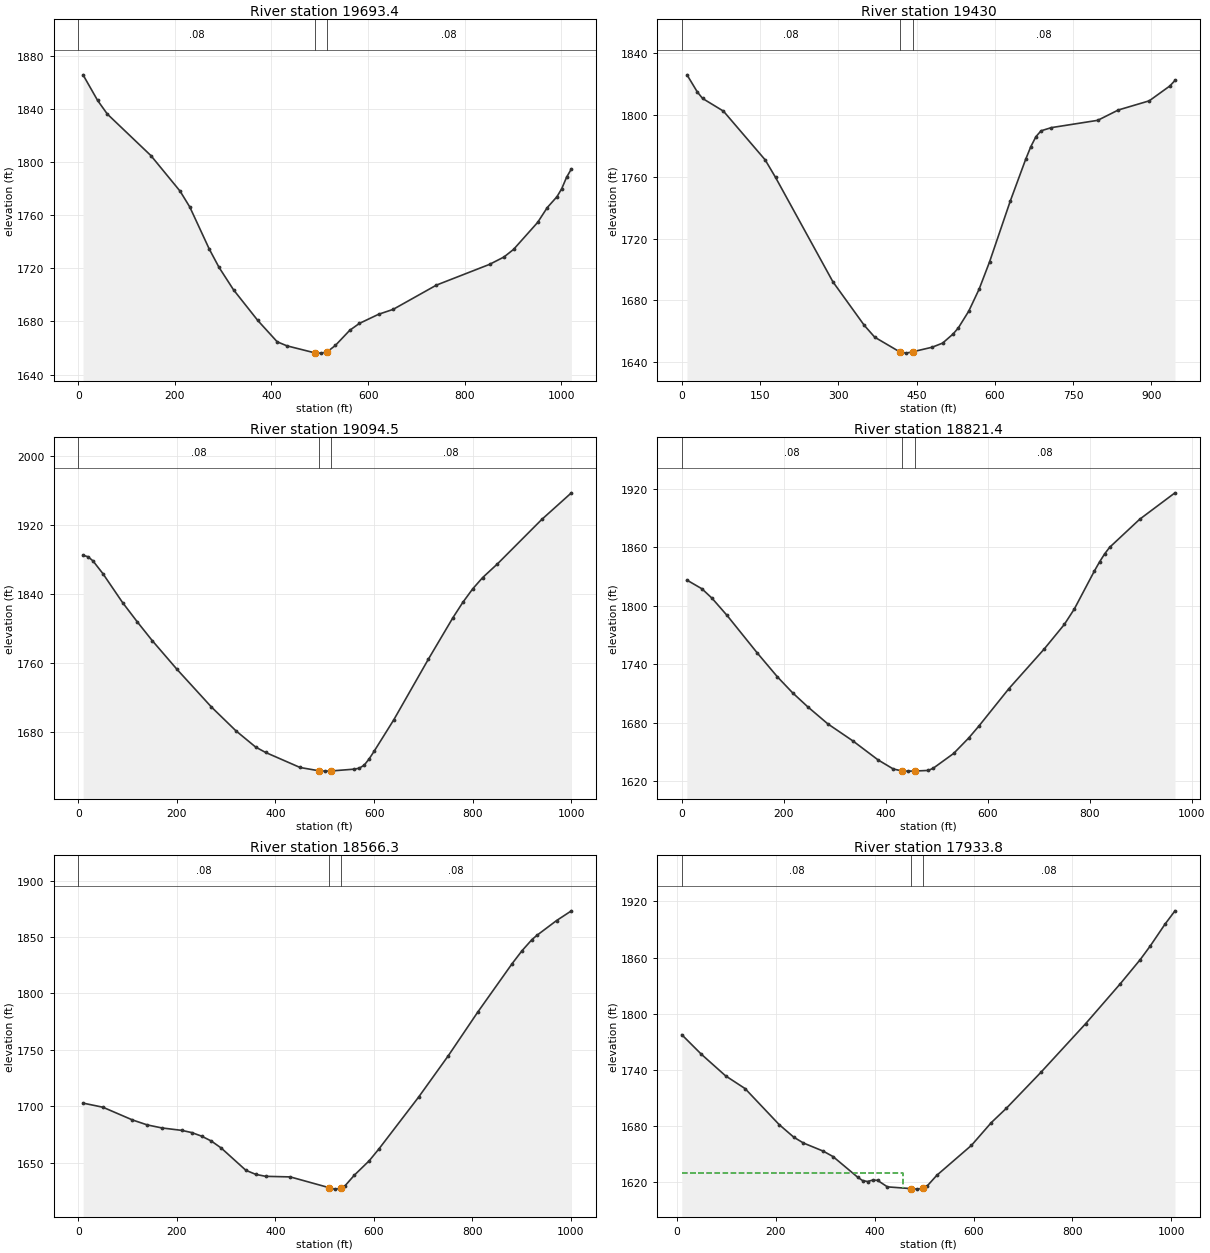
Type RM Length L Ch R = 1 ,19693.4 ,273.6,263.4,253.2
XS GIS Cut Line= 3
     1781717.789      123944.471     1781333.426      124251.875
     1780920.286      124581.478
#Sta/Elev= 30
      10  1865.5    40.2 1846.23    60.3 1835.99   150.7 1804.67   210.9 1777.99
     231 1766.05   271.2  1734.5   291.3 1720.79   321.4 1703.84   371.6 1680.78
   411.8 1664.73   431.9 1661.68   489.6  1656.4   502.1 1656.19   514.6 1656.96
   532.1 1661.93     562 1673.37   581.9 1678.53   621.8 1685.43   651.7 1689.08
   741.5 1707.37   851.2 1722.93   881.1 1728.48     901  1734.2   950.9 1754.53
   970.8 1765.69   990.8 1773.82  1000.7 1779.87  1010.7 1788.45  1020.7 1794.77
#Mann= 3 , 0 , 0
       0     .08       0   489.6    .045       0   514.6     .08       0
Bank Sta=489.6,514.6
XS Rating Curve= 0 ,0
Exp/Cntr=0.3,0.1

Type RM Length L Ch R = 1 ,19430   ,334.3,335.5,336.7
XS GIS Cut Line= 4
     1781388.498      123712.939     1781234.143      123934.181
     1781074.643       124212.02     1780873.982      124505.294
#Sta/Elev= 30
      10 1826.13      30 1814.91      40 1810.81    79.9 1802.61   159.9 1771.03
   179.8 1759.66   289.8 1692.04   349.9 1663.86   369.9  1656.2   417.4 1646.78
   429.9 1645.88   442.4 1646.73     480 1649.71     500 1652.37   520.1 1658.27
   530.1 1662.19   550.1 1673.04   570.1 1687.38   590.1 1705.05   629.6 1744.24
   659.2 1771.35   669.1 1779.59     679 1786.12   688.8 1789.88   708.6 1791.94
   797.4 1796.66   836.9 1803.36   896.1 1809.28   935.6  1818.9   945.5 1822.48
#Mann= 3 , 0 , 0
       0     .08       0   417.4    .045       0   442.4     .08       0
Bank Sta=417.4,442.4
XS Rating Curve= 0 ,0
Exp/Cntr=0.3,0.1

Type RM Length L Ch R = 1 ,19094.5 ,269,273.2,277.1
XS GIS Cut Line= 3
     1781185.542      123535.078     1780857.049      123976.188
     1780585.853      124335.504
#Sta/Elev= 30
      10 1885.19      20 1883.56      30 1878.71      50 1864.02      90 1830.35
     120 1807.82     150 1786.28     200 1753.04     270 1709.17     320 1681.37
     360 1662.49     380 1656.32     450 1638.83   487.5 1635.09     500 1634.61
   512.5 1634.78     560 1636.91     570 1638.04     580 1641.55     590  1648.8
     600 1657.56     640 1694.22     710 1764.49   760.1 1812.94   780.1 1830.67
   800.1  1846.3   820.1  1859.3   850.1 1875.19   940.1 1926.86  1000.2 1957.78
#Mann= 3 , 0 , 0
       0     .08       0   487.5    .045       0   512.5     .08       0
Bank Sta=487.5,512.5
XS Rating Curve= 0 ,0
Exp/Cntr=0.3,0.1

Type RM Length L Ch R = 1 ,18821.4 ,258.7,255.1,249.4
XS GIS Cut Line= 4
     1780925.433      123352.777     1780796.804      123630.616
     1780621.869      123857.003     1780452.078      124191.439
#Sta/Elev= 30
     9.9 1826.38    39.5 1817.42    59.3 1807.77    88.9 1790.07   148.1 1751.62
   187.7  1727.1   217.3 1710.86   246.9 1696.56   286.4 1679.01   335.8 1661.46
   385.1 1642.02   414.7 1632.81   431.8 1630.73   444.3 1630.57   456.8 1630.65
   483.7  1631.3   493.6  1633.7   533.1 1648.64   562.7 1664.49   582.4 1676.56
   641.6 1715.13   710.7 1755.64   750.2 1780.83   769.9 1796.72   809.4  1835.8
   819.3 1844.89   829.2 1853.05     839 1859.84   898.2 1888.73   967.3 1915.75
#Mann= 3 , 0 , 0
       0     .08       0   431.8    .045       0   456.8     .08       0
Bank Sta=431.8,456.8
XS Rating Curve= 0 ,0
Exp/Cntr=0.3,0.1

Type RM Length L Ch R = 1 ,18566.3 ,637,632.5,627.9
XS GIS Cut Line= 3
     1780726.299        123189.8     1780493.824      123633.117
     1780268.331      124079.928
#Sta/Elev= 30
      10 1702.76    50.1 1699.13   110.1 1687.86   140.2 1683.44   170.2 1680.74
   210.2 1678.61   230.3 1676.67   250.3 1673.53   270.3 1669.13   290.3 1662.97
   340.4  1643.2   360.4 1639.62   380.4 1637.88   430.5 1637.36   508.1 1627.96
   520.6 1626.53   533.1 1627.21   540.6 1628.98   560.6 1638.94   590.7 1651.68
   610.7 1662.33   690.8 1708.01   750.8 1744.51   810.9 1783.38   880.9 1826.46
     901 1837.93     921  1847.7     931 1851.46     971 1864.59  1001.1 1873.21
#Mann= 3 , 0 , 0
       0     .08       0   508.1    .045       0   533.1     .08       0
Bank Sta=508.1,533.1
XS Rating Curve= 0 ,0
Exp/Cntr=0.3,0.1

Type RM Length L Ch R = 1 ,17933.8 ,309.3,306.9,304.5
XS GIS Cut Line= 4
     1780091.427      122990.705      1779972.42      123217.186
     1779886.156       123514.71     1779729.782      123927.745
#Sta/Elev= 30
     9.8 1777.39    49.2 1756.58    98.4 1733.36   137.8 1719.73   206.6 1681.27
   236.2 1667.77   255.8 1661.48   295.8 1652.81   315.8 1646.94   365.8 1624.78
   375.8  1621.2   385.8 1620.28   395.7 1621.79   405.7 1621.54   425.7 1614.55
   473.2  1612.7   485.7 1612.13   498.2 1613.18   505.7 1615.24   525.6 1626.93
   595.7    1659   635.9 1683.37     666 1698.52   736.3 1737.23   826.6 1789.18
   896.9 1832.04     937 1857.74   957.1  1872.2   987.2 1895.74  1007.3 1909.95
#Mann= 3 , 0 , 0
     9.8     .08       0   473.2    .045       0   498.2     .08       0
#XS Ineff= 2 , 0
          457.03  1629.3
Permanent Ineff=
       F       F
Bank Sta=473.2,498.2
XS Rating Curve= 0 ,0
Exp/Cntr=0.3,0.1

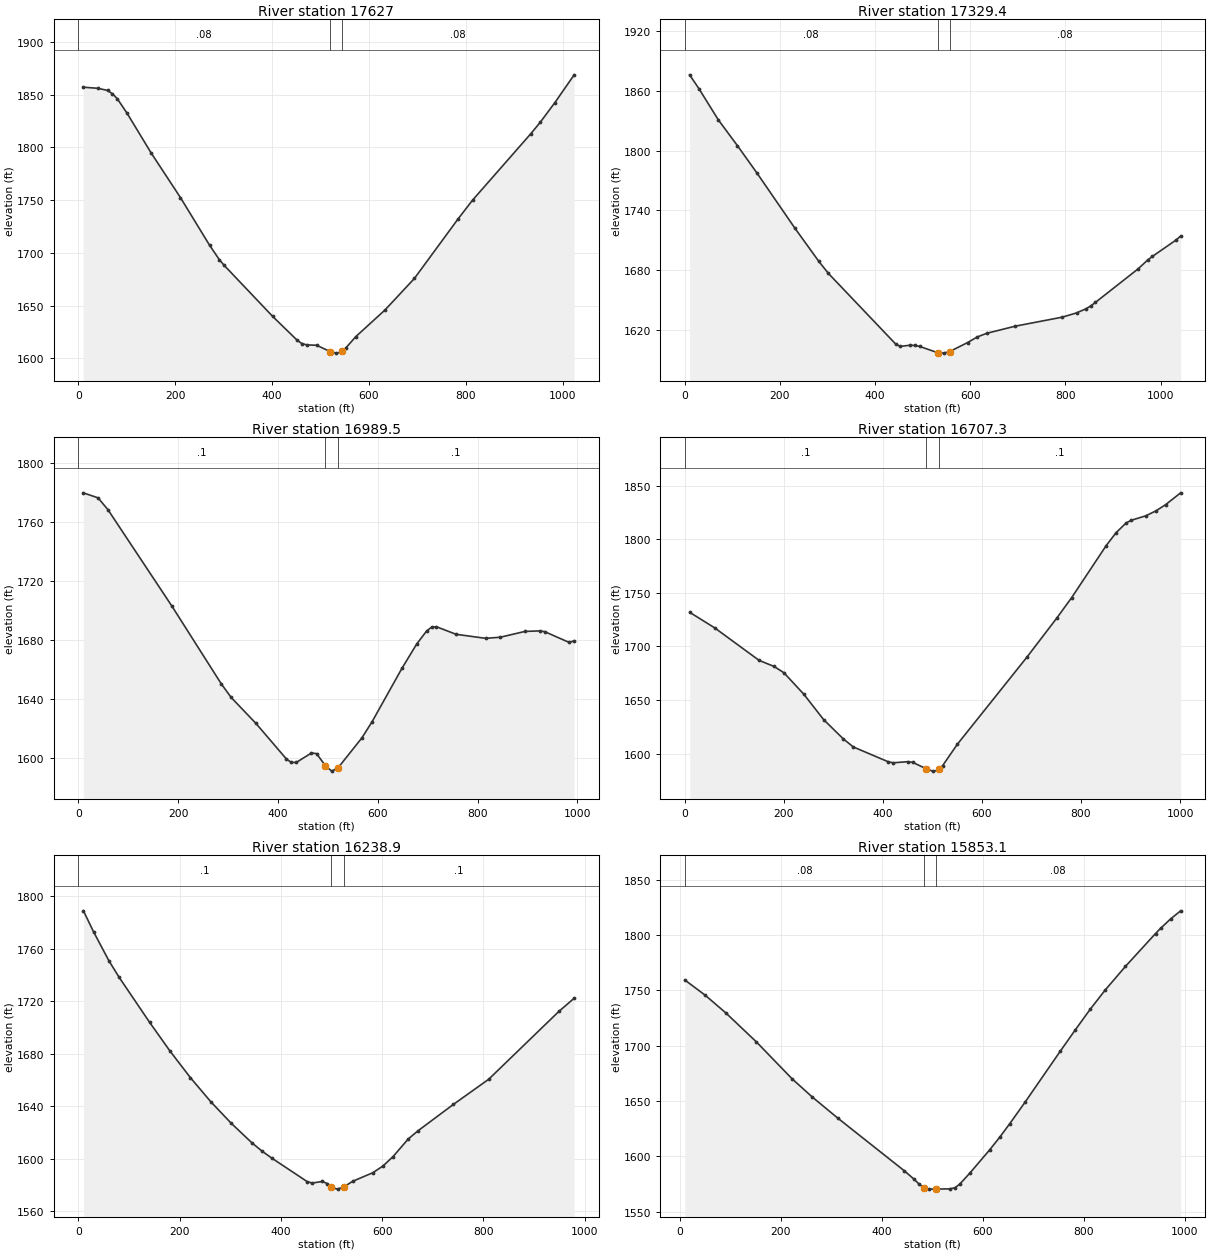
Type RM Length L Ch R = 1 ,17627   ,276.3,297.5,318.8
XS GIS Cut Line= 4
     1779839.804      122874.277     1779639.142      123244.729
     1779587.691      123501.987     1779582.546      123841.568
#Sta/Elev= 30
      10 1857.15    40.1 1856.12    60.2 1854.11    70.2 1851.02    80.2 1846.35
   100.3 1832.69   150.5 1794.65   210.7 1752.53   270.8 1707.37   290.9 1693.73
   300.9 1688.29   401.2 1639.77   451.6 1617.28   461.7 1613.98   471.8 1612.84
   491.9 1612.47   519.8 1606.48   532.3 1605.02   542.4 1605.91   544.8 1606.92
   552.5 1610.18   572.7 1620.68   633.2 1646.06   693.6 1675.84   783.5 1732.13
   813.5    1750   933.4 1812.81   953.4 1823.94   983.3  1842.4  1023.3 1868.88
#Mann= 3 , 0 , 0
       0     .08       0   519.8    .045       0   544.8     .08       0
Bank Sta=519.8,544.8
XS Rating Curve= 0 ,0
Exp/Cntr=0.3,0.1

Type RM Length L Ch R = 1 ,17329.4 ,346.9,339.9,332.9
XS GIS Cut Line= 4
     1779747.191      122853.696     1779493.345      123139.724
     1779304.092      123273.962     1778987.806      123561.688
#Sta/Elev= 30
    10.1 1876.08    30.2 1861.83    70.4  1830.9   110.7  1804.9     151 1777.92
   231.5 1722.01   281.8 1688.66   301.9 1676.62     443 1605.83     453 1603.39
   473.2 1604.57   483.3 1604.36   493.4 1603.39   531.3 1597.08   543.8 1596.63
   556.3 1598.11   594.3 1607.24   614.5 1612.84   634.3  1616.5     694 1623.65
   793.4 1632.76   823.3 1637.03   843.2 1641.16   853.1    1644     863  1647.6
   952.5 1681.19   972.4 1689.98   982.4 1693.66  1032.1  1710.1    1042 1714.16
#Mann= 3 , 0 , 0
       0     .08       0   531.3    .045       0   556.3     .08       0
Bank Sta=531.3,556.3
XS Rating Curve= 0 ,0
Exp/Cntr=0.3,0.1

Type RM Length L Ch R = 1 ,16989.5 ,286.4,282.2,277.5
XS GIS Cut Line= 4
     1779438.481      122632.454     1779232.674      122910.293
     1779047.449      123110.954     1778821.061      123409.374
#Sta/Elev= 30
     9.9 1779.79    39.5 1776.38    59.3 1768.38   187.7 1702.89   286.5 1650.29
   306.2 1641.12   355.9 1623.52   416.6 1599.52   426.7 1597.05   436.8 1597.09
   467.1  1603.5   477.2 1603.06   495.1 1594.83   507.6 1591.19   520.1 1593.31
   568.3 1613.81   588.5 1624.65   648.4 1660.87     678 1677.36   697.7 1686.11
   707.6 1688.72   717.4 1689.05   756.8 1683.92     816 1681.18   845.6 1681.94
   894.8 1685.87   924.4 1686.22   934.3 1685.72   983.6 1678.38   993.4 1679.53
#Mann= 3 , 0 , 0
       0      .1       0   495.1    .045       0   520.1      .1       0
Bank Sta=495.1,520.1
XS Rating Curve= 0 ,0
Exp/Cntr=0.3,0.1

Type RM Length L Ch R = 1 ,16707.3 ,460.4,468.4,476.9
XS GIS Cut Line= 3
     1779183.418      122436.776     1778904.589      122852.389
      1778633.87      123273.493
#Sta/Elev= 30
      10 1731.76    60.1 1717.36   150.1 1686.92   180.2 1681.31   200.2 1675.38
   240.2 1655.44   280.3 1631.68   320.3 1613.59   340.3 1606.16   410.4 1592.42
   420.4 1591.38   450.4 1592.44   460.4 1591.77     488 1585.68   500.5 1583.62
   510.5 1584.25     513 1585.37   520.5 1588.72   550.5 1608.82   690.7 1689.92
   750.8 1726.25   780.8 1745.29   850.9 1794.08   870.9 1806.15     891 1815.13
     901 1817.58     931 1821.87     951 1826.37   971.1 1832.33  1001.1 1843.27
#Mann= 3 , 0 , 0
       0      .1       0     488    .045       0     513      .1       0
Bank Sta=488,513
XS Rating Curve= 0 ,0
Exp/Cntr=0.3,0.1

Type RM Length L Ch R = 1 ,16238.9 ,379.9,385.8,391.6
XS GIS Cut Line= 4
     1778979.084      122225.399     1778691.506      122428.911
     1778461.003        122619.9     1778253.616      122873.689
#Sta/Elev= 30
    10.1 1789.06    30.2 1772.99    60.4 1750.99    80.5 1738.41   140.9 1703.98
   181.2 1682.06   221.4 1661.83   261.7 1643.46     302 1627.06   342.2 1612.38
   362.3 1605.97   382.2 1600.47   452.1 1582.55   462.1 1581.47     482 1582.69
     492 1581.02   499.5 1578.65     502 1577.87     512 1576.83   524.5 1578.56
   541.9 1582.81   581.8 1589.35   601.8 1594.48   621.7 1601.67   651.7  1615.1
   671.5 1621.48     741 1641.48   810.6 1660.62   949.6 1712.49   979.4 1722.39
#Mann= 3 , 0 , 0
       0      .1       0   499.5    .045       0   524.5      .1       0
Bank Sta=499.5,524.5
XS Rating Curve= 0 ,0
Exp/Cntr=0.3,0.1

Type RM Length L Ch R = 1 ,15853.1 ,278,278.5,279
XS GIS Cut Line= 3
     1778856.151      121997.541     1778432.568      122188.667
      1777970.36      122442.083
#Sta/Elev= 30
    10.1 1759.33    50.5 1745.57    90.9 1729.77   151.5 1703.58   222.3  1670.2
   262.7 1653.57   313.2 1634.55   444.5 1587.14   464.7  1579.2   474.7 1574.69
   484.6 1571.47   494.5  1570.5     507 1570.55   534.3 1570.73   544.3  1571.6
   554.2 1574.88   574.1 1584.77   613.9 1606.05   633.8 1617.47   653.7 1629.73
   683.5 1648.81   753.1 1694.77     783 1714.12   812.8  1732.9   842.6 1750.33
   882.4  1771.5   942.1 1801.26     952 1805.89   971.9 1814.43   991.8 1821.76
#Mann= 3 , 0 , 0
    10.1     .08       0   484.6    .045       0     507     .08       0
Bank Sta=484.6,507
XS Rating Curve= 0 ,0
Exp/Cntr=0.3,0.1

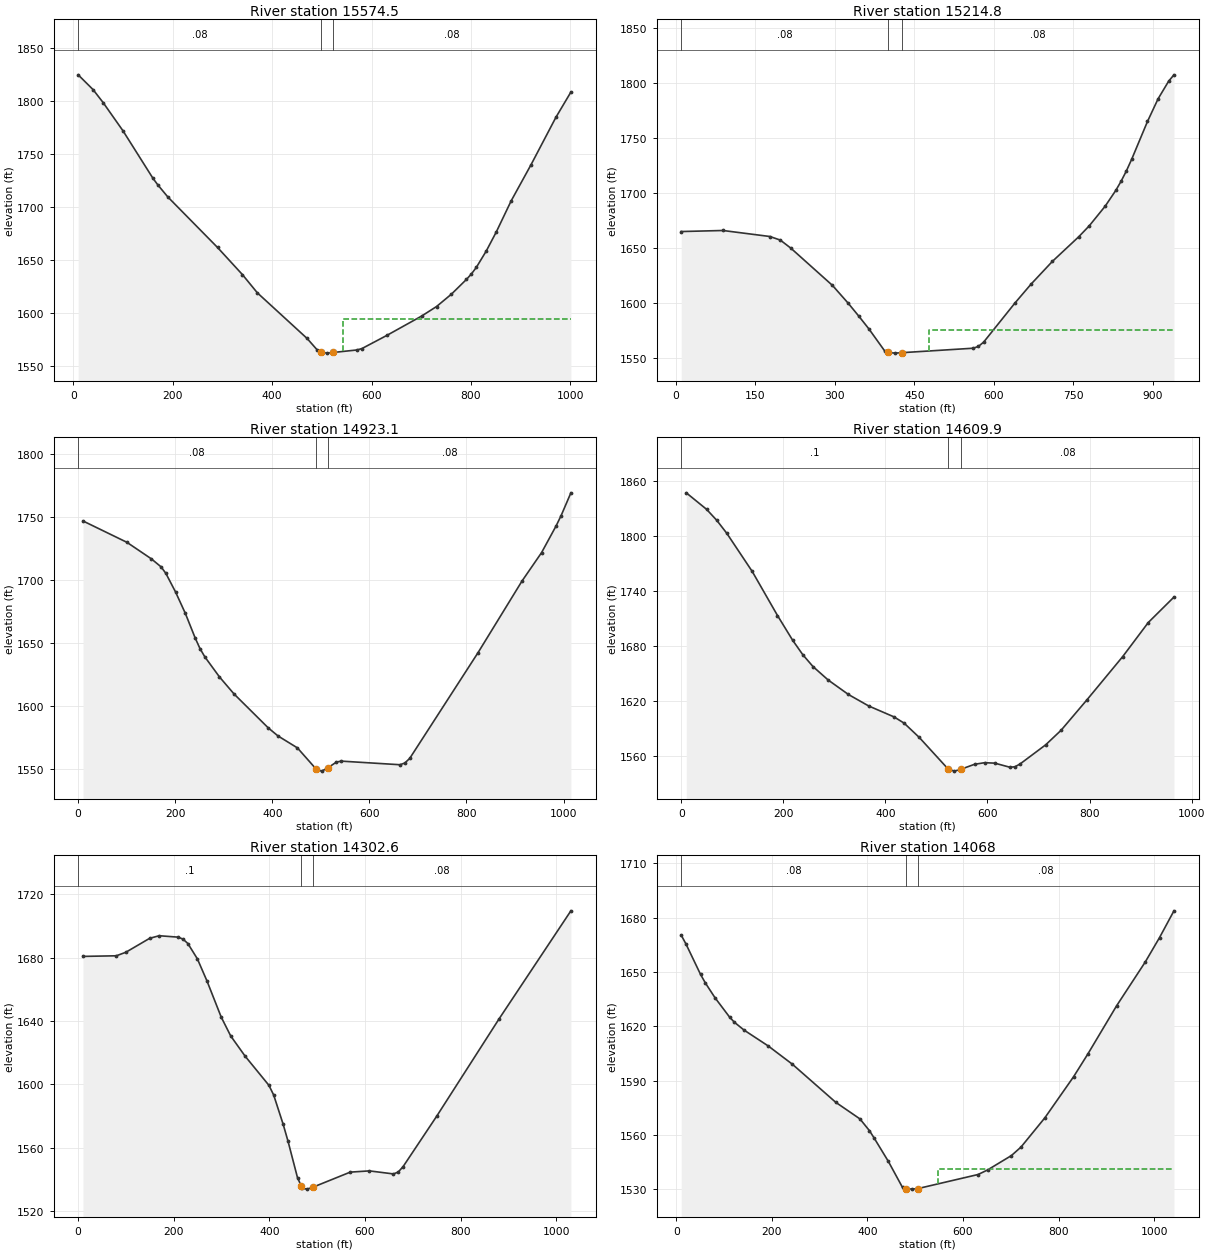
Type RM Length L Ch R = 1 ,15574.5 ,368.5,359.7,348.1
XS GIS Cut Line= 3
     1778700.551      121740.246     1778256.528      121971.219
     1777812.817      122202.772
#Sta/Elev= 30
      10 1824.95      40 1810.96    60.1 1798.79   100.1 1772.07   160.2 1727.32
   170.2 1720.94   190.2 1709.61   290.3 1661.81   340.3 1636.21   370.4 1618.94
   470.5 1575.82   490.5 1565.15     498 1563.08   510.5 1561.98     523 1562.59
   570.6 1564.97   580.6 1566.26   630.6 1578.67   700.7 1596.99   730.7 1605.98
   760.8 1617.74   790.8 1631.57   800.8 1636.77   810.8 1642.98   830.8  1658.5
   850.9 1676.44   880.9  1705.9   920.9 1740.08     971 1784.92    1001 1808.67
#Mann= 3 , 0 , 0
      10     .08       0     498    .045       0     523     .08       0
#XS Ineff= 2 , 0
                          542.24         1593.93
Permanent Ineff=
       F       F
Bank Sta=498,523
XS Rating Curve= 0 ,0
Exp/Cntr=0.3,0.1

Type RM Length L Ch R = 1 ,15214.8 ,309.8,291.7,276.5
XS GIS Cut Line= 4
     1778357.996      121371.889      1778164.17      121594.888
     1777941.238      121788.647     1777750.867      122081.922
#Sta/Elev= 30
     9.8 1664.96    88.6 1665.91   177.3 1660.44     197 1657.17   216.7  1649.9
   295.5  1615.9     325 1599.81   344.7 1588.24   364.4 1576.25   393.9 1556.39
   401.1 1554.92   413.6 1554.26   426.1 1554.65   561.3 1558.73   571.1 1560.36
     581 1564.25   640.8 1600.24   670.7 1617.13   710.7 1637.69   760.7 1660.22
   780.6  1670.2   810.6 1688.05   830.6 1702.36   840.6 1710.68   850.6  1720.1
   860.6 1730.68   890.5 1765.15   910.5 1785.76   930.5 1801.85   940.5 1807.64
#Mann= 3 , 0 , 0
     9.8     .08       0   401.1    .045       0   426.1     .08       0
#XS Ineff= 2 , 0
                          478.33         1575.35
Permanent Ineff=
       F       F
Bank Sta=401.1,426.1
XS Rating Curve= 0 ,0
Exp/Cntr=0.3,0.1

Type RM Length L Ch R = 1 ,14923.1 ,310.6,313.2,315.8
XS GIS Cut Line= 3
     1777914.614      121026.753     1777838.074      121522.814
     1777760.259       122030.06
#Sta/Elev= 30
      10 1746.79   100.4  1729.9   150.6 1716.84   170.7 1710.47   180.7 1705.27
   200.8 1690.39   220.8 1673.58   240.9 1654.22     251 1645.65     261  1639.1
   291.1 1623.22   321.2 1609.69   391.5 1582.88   411.6 1576.48   451.7 1566.99
   489.4 1550.57   491.9 1549.58   501.9 1548.58   514.4 1551.23   532.1 1555.76
   542.2  1556.5   662.9 1553.65     673 1555.02   683.1  1558.7   823.9 1642.53
   914.5 1699.29   954.7 1721.74   984.9 1743.09     995 1751.11  1015.1 1769.11
#Mann= 3 , 0 , 0
       0     .08       0   489.4    .045       0   514.4     .08       0
Bank Sta=489.4,514.4
XS Rating Curve= 0 ,0
Exp/Cntr=0.3,0.1

Type RM Length L Ch R = 1 ,14609.9 ,312.7,307.3,301.8
XS GIS Cut Line= 4
     1777677.833      120983.115     1777554.598      121381.428
     1777499.582       121601.49     1777488.579      121922.781
#Sta/Elev= 30
     9.9 1846.65    49.6 1828.71    69.5 1816.78    89.3 1802.53     139 1761.06
   188.6 1712.95   218.4 1685.91   238.3 1670.14   258.1 1657.35   287.9 1642.65
   327.6 1626.87   367.3 1614.36   416.9 1602.47   436.7 1595.64   466.3 1580.11
   522.8 1545.71   535.3 1543.36   547.8 1545.39   574.7 1550.82   594.5 1552.55
   614.2 1552.06   643.8 1547.61   653.8  1548.1   663.9 1551.19   714.1 1572.07
   744.2 1587.89   794.5 1620.82   864.8 1668.11     915  1705.3   965.3 1733.02
#Mann= 3 , 0 , 0
       0      .1       0   522.8    .045       0   547.8     .08       0
Bank Sta=522.8,547.8
XS Rating Curve= 0 ,0
Exp/Cntr=0.3,0.1

Type RM Length L Ch R = 1 ,14302.6 ,241.3,234.5,227.9
XS GIS Cut Line= 3
     1777277.512      120893.389      1777249.47      121351.287
     1777220.915      121922.421
#Sta/Elev= 30
      10 1680.72    79.8  1681.1    99.7 1683.33   149.6 1692.13   169.5 1693.75
   209.4 1692.85   219.4 1691.58   229.4 1688.85   249.3 1679.19   269.3 1665.31
   299.2 1642.44   319.1 1630.54   349.1 1617.86   398.9 1599.47   408.9 1593.34
   428.8 1574.84   438.8 1564.34   458.8 1541.17   466.3 1536.22   468.8 1534.57
   478.8    1534   491.3 1535.25   569.1 1544.72   609.2  1545.5   659.4 1543.58
   669.4 1544.77   679.5 1548.14   749.7 1579.88   880.1 1641.21  1030.6 1709.45
#Mann= 3 , 0 , 0
       0      .1       0   466.3    .045       0   491.3     .08       0
Bank Sta=466.3,491.3
XS Rating Curve= 0 ,0
Exp/Cntr=0.3,0.1

Type RM Length L Ch R = 1 ,14068   ,203.6,174.2,144.8
XS GIS Cut Line= 4
     1777099.604      120912.082     1776998.288      121293.121
     1777048.946      121555.223     1777174.491      121914.237
#Sta/Elev= 30
    10.1 1670.26    20.2  1665.3    50.5 1648.63    60.7 1643.85    80.9 1635.69
   111.2 1625.09   121.3 1622.22   141.5  1617.9   192.1 1609.14   242.6 1599.08
   333.6 1578.02   384.2 1568.87   404.2 1562.35   414.1 1558.25   443.7 1545.42
   473.4 1531.03   480.7 1530.41   493.2 1530.11   505.7 1530.42   631.6 1538.18
   651.3 1540.67   701.3 1548.62   721.3 1553.29   771.3 1569.44   831.4 1592.09
   861.4  1604.7   921.5 1631.26   981.5 1655.44  1011.5 1668.96  1041.6 1683.69
#Mann= 3 , 0 , 0
    10.1     .08       0   480.7    .045       0   505.7     .08       0
#XS Ineff= 2 , 0
                           548.5         1541.14
Permanent Ineff=
       F       F
Bank Sta=480.7,505.7
XS Rating Curve= 0 ,0
Exp/Cntr=0.3,0.1

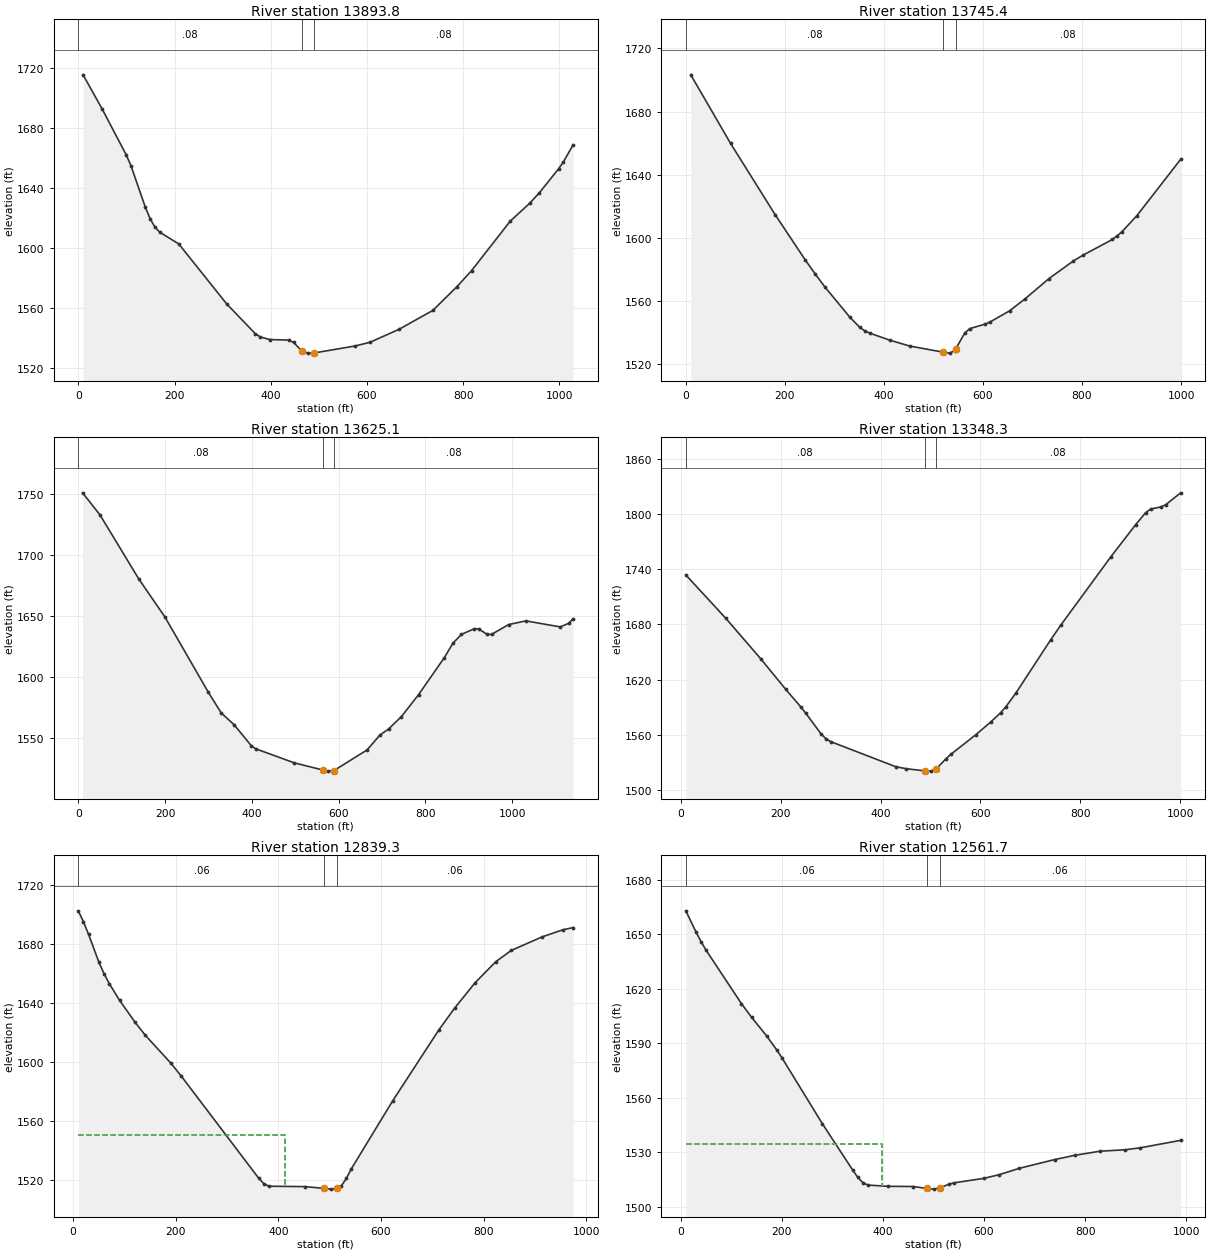
Type RM Length L Ch R = 1 ,13893.8 ,133.8,148.4,163
XS GIS Cut Line= 4
     1776718.363      121053.438     1776802.185      121442.612
      1776969.83      121502.485     1777135.478      121923.591
#Sta/Elev= 30
      10 1715.33    49.8 1692.47    99.5 1662.13   109.5 1654.85   139.3 1627.29
   149.3 1619.56   159.2 1614.05   169.2  1610.6     209 1602.72   308.5 1562.83
   368.2 1542.94   378.2 1540.85   398.1 1539.12   437.7 1538.74   447.5 1537.22
   464.7 1531.47   477.2 1530.07   489.7 1530.15   576.1 1534.88   606.3 1537.28
   666.6 1545.91     737 1558.51   787.3 1574.38   817.5    1585   897.9 1617.93
   938.1 1629.76   958.2 1636.72   998.5 1652.82  1008.5 1657.42  1028.6 1668.75
#Mann= 3 , 0 , 0
       0     .08       0   464.7    .045       0   489.7     .08       0
Bank Sta=464.7,489.7
XS Rating Curve= 0 ,0
Exp/Cntr=0.3,0.1

Type RM Length L Ch R = 1 ,13745.4 ,100.9,120.4,139.8
XS GIS Cut Line= 4
     1776628.554      121103.332     1776778.236      121540.405
     1776923.927      121708.049     1777073.609       121985.46
#Sta/Elev= 30
      10 1703.26    90.4 1659.81   180.8 1614.53     241 1586.16   261.1 1577.27
   281.2 1568.82   331.4 1549.76   351.5 1543.34   361.6 1541.16   371.6 1539.72
   411.8  1535.3   451.9 1531.59   520.2 1527.66   532.7 1527.09   542.8 1528.65
   545.2 1529.91   562.9 1539.61     573 1542.57   603.3 1545.35   613.4 1546.65
   653.8 1553.87   684.1 1561.21   733.3 1574.27   782.6 1585.44   802.3 1589.14
   861.4 1599.03   871.3 1601.44   881.1 1604.04   910.7 1614.05   999.3 1649.78
#Mann= 3 , 0 , 0
       0     .08       0   520.2    .045       0   545.2     .08       0
Bank Sta=520.2,545.2
XS Rating Curve= 0 ,0
Exp/Cntr=0.3,0.1

Type RM Length L Ch R = 1 ,13625.1 ,277.1,276.8,276.5
XS GIS Cut Line= 4
     1776520.097      121103.656     1776707.552      121374.615
     1776718.565      121740.236      1777056.27       122030.47
#Sta/Elev= 30
      10 1751.34    49.9 1733.28   139.8 1680.46   199.7 1649.45   299.5 1587.82
   329.5 1570.71   359.1 1561.04   398.7 1543.85   408.6 1541.31   497.5 1529.76
   564.1 1523.81   576.6 1522.93   589.1 1523.36   665.6 1540.31   695.3 1552.53
   715.1 1557.49   744.7 1567.62   784.3 1585.69   843.7 1616.05   863.5 1627.92
   883.3 1635.16     913 1639.84   922.9 1639.63   942.7 1635.12   952.5 1635.15
   992.1 1643.23  1031.7 1646.25  1110.9 1641.29  1130.7 1644.29  1140.6 1648.08
#Mann= 3 , 0 , 0
       0     .08       0   564.1    .045       0   589.1     .08       0
Bank Sta=564.1,589.1
XS Rating Curve= 0 ,0
Exp/Cntr=0.3,0.1

Type RM Length L Ch R = 1 ,13348.3 ,509.6,509,508.3
XS GIS Cut Line= 3
     1776420.409      121117.948     1776440.413      121618.049
     1776460.417      122118.149
#Sta/Elev= 30
      10 1733.62    90.1 1686.51   160.2 1642.47   210.2 1609.32   240.2 1590.34
   250.3 1583.45   280.3 1561.43   290.3 1555.88   300.3 1552.62   430.4 1525.42
   450.5 1523.34     488  1520.9   500.5 1520.63   510.5  1522.6   530.5 1533.77
   540.5 1538.77   590.6 1560.07   620.6 1573.96   640.6 1584.14   650.7 1590.32
   670.7 1605.15   740.7 1663.22   760.8 1679.05   860.9 1753.14   910.9 1788.29
   930.9 1801.27   940.9  1805.2     961 1807.41     971 1809.87    1001 1822.78
#Mann= 3 , 0 , 0
      10     .08       0     488    .045       0   510.5     .08       0
Bank Sta=488,510.5
XS Rating Curve= 0 ,0
Exp/Cntr=0.3,0.1

Type RM Length L Ch R = 1 ,12839.3 ,277.2,277.6,278.3
XS GIS Cut Line= 2
     1775903.753      121150.647     1775965.495      122123.083
#Sta/Elev= 30
      10 1702.47    20.1 1695.05    30.1 1686.48    50.2 1667.68    60.3 1659.77
    70.3 1653.19    90.4 1641.88   120.5 1627.04   140.6 1618.16   190.9 1599.07
     211 1590.36   361.6 1521.29   371.7 1517.56   381.7 1515.86     452  1515.6
   489.8 1514.38   502.3  1513.9   514.8 1514.44   522.4 1515.95   532.4 1521.12
   542.4  1527.8   622.8 1573.75   713.2 1622.03   743.4 1636.51   783.5 1653.81
   823.7    1668   853.9 1675.65   914.1 1684.83   954.3 1689.61   974.4 1691.12
#Mann= 3 , 0 , 0
      10     .06       0   489.8    .045       0   514.8     .06       0
#XS Ineff= 2 , 0
          412.64  1550.7
Permanent Ineff=
       F       F
Bank Sta=489.8,514.8
XS Rating Curve= 0 ,0
Exp/Cntr=0.3,0.1

Type RM Length L Ch R = 1 ,12561.7 ,369.3,369.6,369.5
XS GIS Cut Line= 3
     1775633.488      121175.692     1775662.147      121654.947
     1775679.795      122163.563
#Sta/Elev= 30
      10 1662.84      30 1651.28      40 1645.95      50 1641.21     120 1611.79
     140 1604.32     170 1593.96     190 1586.28     200 1582.06   280.1 1545.74
   340.1 1520.25   350.1 1516.26   360.1 1513.36   370.1 1511.99   410.1  1511.3
   460.1 1511.18   487.6  1510.1   500.1 1509.75   512.6 1510.44     530  1512.4
     540 1513.19   599.9  1515.7   629.8 1517.68   669.7  1521.2   739.6    1526
   779.5 1528.36   829.4 1530.61   879.3  1531.4   909.2 1532.49     989 1536.59
#Mann= 3 , 0 , 0
      10     .06       0   487.6    .045       0   512.6     .06       0
#XS Ineff= 2 , 0
          398.99 1534.33
Permanent Ineff=
       F       F
Bank Sta=487.6,512.6
XS Rating Curve= 0 ,0
Exp/Cntr=0.3,0.1

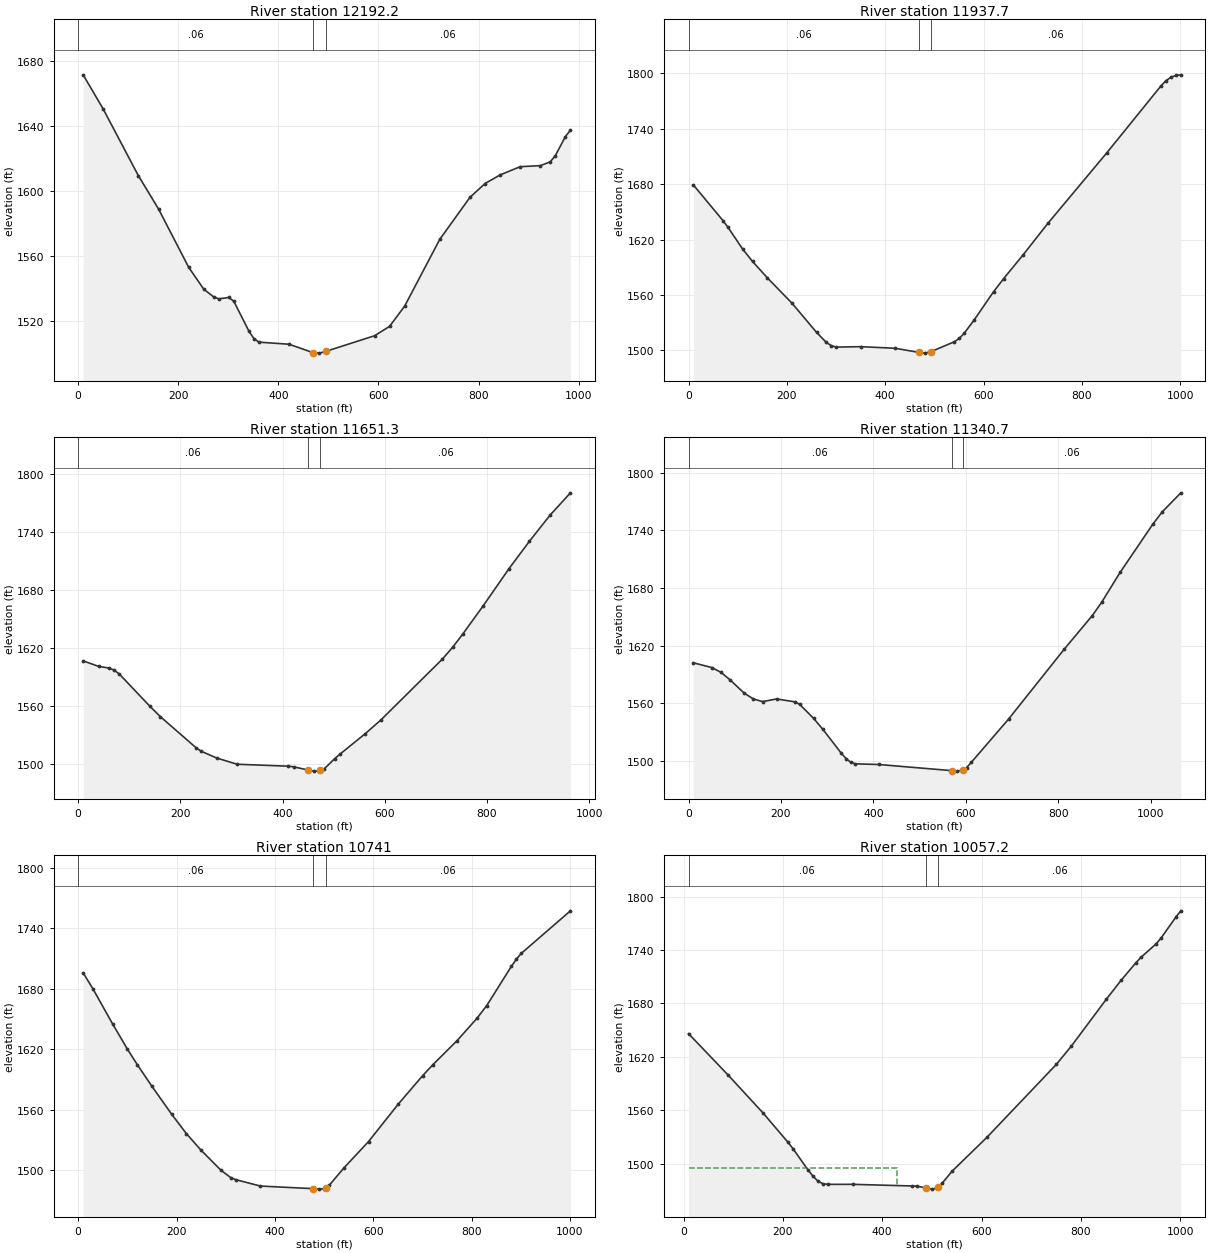
Type RM Length L Ch R = 1 ,12192.2 ,255.3,254.5,253.6
XS GIS Cut Line= 2
     1775276.043      121176.373     1775317.204      122159.099
#Sta/Elev= 30
      10 1671.45    50.2  1650.3   120.4 1609.27   160.6 1588.81   220.8 1552.92
   250.9 1539.44     271 1534.59     281 1533.44   301.1 1534.31   311.1 1531.92
   341.2 1513.57   351.3 1508.93   361.3 1506.78   421.5  1505.5   469.3 1500.31
   481.8 1500.02   494.3 1501.05   592.2 1510.73   622.3 1516.52   652.4 1529.01
   722.6 1570.15   782.9    1596     813  1604.5   843.1  1609.8   883.2 1614.87
   923.4  1615.5   943.4 1617.89   953.5 1621.71   973.6 1633.45   983.6 1637.36
#Mann= 3 , 0 , 0
       0     .06       0   469.3    .045       0   494.3     .06       0
Bank Sta=469.3,494.3
XS Rating Curve= 0 ,0
Exp/Cntr=0.3,0.1

Type RM Length L Ch R = 1 ,11937.7 ,285.9,286.4,287
XS GIS Cut Line= 3
     1775006.077      121177.305     1775043.054      121676.437
     1775080.032      122175.569
#Sta/Elev= 30
      10 1679.07    70.1  1640.5    80.1 1633.39   110.1  1609.7   130.1 1596.42
   160.2 1578.63   210.2 1551.27   260.3 1519.61   280.3 1508.64   290.3 1505.23
   300.3 1503.65   350.4 1504.11   420.4 1502.37     468 1497.95   480.5 1497.12
     493  1498.7   540.5 1509.43   550.6 1513.04   560.6 1518.67   580.6 1532.83
   620.6 1563.78   640.6 1577.65   680.7 1603.72   730.7 1637.55   850.9 1714.12
     961 1786.53     971 1791.99     981 1795.73     991 1797.59    1001 1798.29
#Mann= 3 , 0 , 0
       0     .06       0     468    .045       0     493     .06       0
Bank Sta=468,493
XS Rating Curve= 0 ,0
Exp/Cntr=0.3,0.1

Type RM Length L Ch R = 1 ,11651.3 ,313,310.6,308.7
XS GIS Cut Line= 2
     1774730.656      121202.098     1774782.107      122164.244
#Sta/Elev= 30
      10 1606.71    40.1 1601.07    60.2 1599.36    70.3 1597.26    80.3  1593.3
   140.5 1559.83   160.6 1549.27   230.8 1517.01   240.9 1513.36     271 1506.43
   311.1 1499.96   411.5 1497.93   421.5 1497.33   449.2 1494.08   461.7 1492.84
   471.7 1492.93   474.2 1493.52   481.8 1495.29   501.8 1505.54   511.9 1510.15
   562.1 1531.63   592.2 1545.56   712.6 1608.47   732.7 1620.65   752.8 1634.48
   792.9 1663.78   843.1 1701.96   883.2 1730.37   923.4  1757.2   963.5 1780.42
#Mann= 3 , 0 , 0
       0     .06       0   449.2    .045       0   474.2     .06       0
Bank Sta=449.2,474.2
XS Rating Curve= 0 ,0
Exp/Cntr=0.3,0.1

Type RM Length L Ch R = 1 ,11340.7 ,601.1,599.6,597.6
XS GIS Cut Line= 3
     1774365.349      121135.211     1774452.457      121720.479
     1774514.559       122189.97
#Sta/Elev= 30
      10 1602.23    50.1 1597.27    70.2 1592.29    90.3 1584.26   120.3 1570.63
   140.4  1564.5   160.5 1561.77   190.6 1564.52   230.7 1561.49   240.7 1558.81
   270.8 1544.23   290.8 1532.81     331 1507.75     341 1502.38     351 1498.53
     361 1496.94   411.2 1496.25   569.2 1489.85   581.7 1489.33   594.2 1490.63
   601.8 1493.02   611.9 1498.43   692.5  1543.5   813.4 1616.58   873.8 1651.37
     894 1665.19   934.3 1696.59  1004.8 1746.61    1025 1759.29  1065.3 1779.24
#Mann= 3 , 0 , 0
       0     .06       0   569.2    .045       0   594.2     .06       0
Bank Sta=569.2,594.2
XS Rating Curve= 0 ,0
Exp/Cntr=0.3,0.1

Type RM Length L Ch R = 1 ,10741   ,688.1,683.8,680
XS GIS Cut Line= 3
     1773762.214      121309.236     1773860.364      121799.993
     1773961.081      122290.396
#Sta/Elev= 30
      10 1696.01      30 1680.03    70.1 1645.23   100.1  1620.3   120.1 1604.98
   150.1 1583.37   190.2 1555.73   220.2 1536.46   250.2 1519.93   290.3 1500.31
   310.3 1492.93   320.3 1490.93   370.4 1484.58     478 1481.98   490.5 1481.52
   500.5 1482.06     503 1482.86   510.5 1485.25   540.5 1502.58   590.6 1528.71
   650.7 1565.62   700.7 1594.04   720.8 1604.56   770.8  1628.8   810.9 1650.73
   830.9 1663.43     881 1702.29     891 1709.28     901 1715.11  1001.1 1757.33
#Mann= 3 , 0 , 0
       0     .06       0     478    .045       0     503     .06       0
Bank Sta=478,503
XS Rating Curve= 0 ,0
Exp/Cntr=0.3,0.1

Type RM Length L Ch R = 1 ,10057.2 ,493.8,489.6,485.1
XS GIS Cut Line= 3
     1773037.641      121535.221      1773210.87      122004.865
     1773376.775      122477.054
#Sta/Elev= 30
      10 1646.07    90.1 1599.31   160.2 1556.81   210.2 1524.03   220.3 1516.82
   250.3 1493.12   260.3 1486.03   270.3  1480.5   280.3 1477.47   290.3 1476.71
   340.4 1476.74   460.5 1474.89   470.5 1474.65   488.1 1472.67   500.6 1471.35
   510.6 1472.71   513.1 1474.02   520.6 1477.96   540.6 1491.46   610.7 1529.52
   750.8 1611.67   780.8 1632.08   850.9 1684.51   880.9 1705.96     911  1725.9
     921 1731.84     951 1746.75     961 1753.24   991.1 1776.95  1001.1 1784.05
#Mann= 3 , 0 , 0
      10     .06       0   488.1    .045       0   513.1     .06       0
#XS Ineff= 2 , 0
          430.34 1494.96
Permanent Ineff=
       F       F
Bank Sta=488.1,513.1
XS Rating Curve= 0 ,0
Exp/Cntr=0.3,0.1