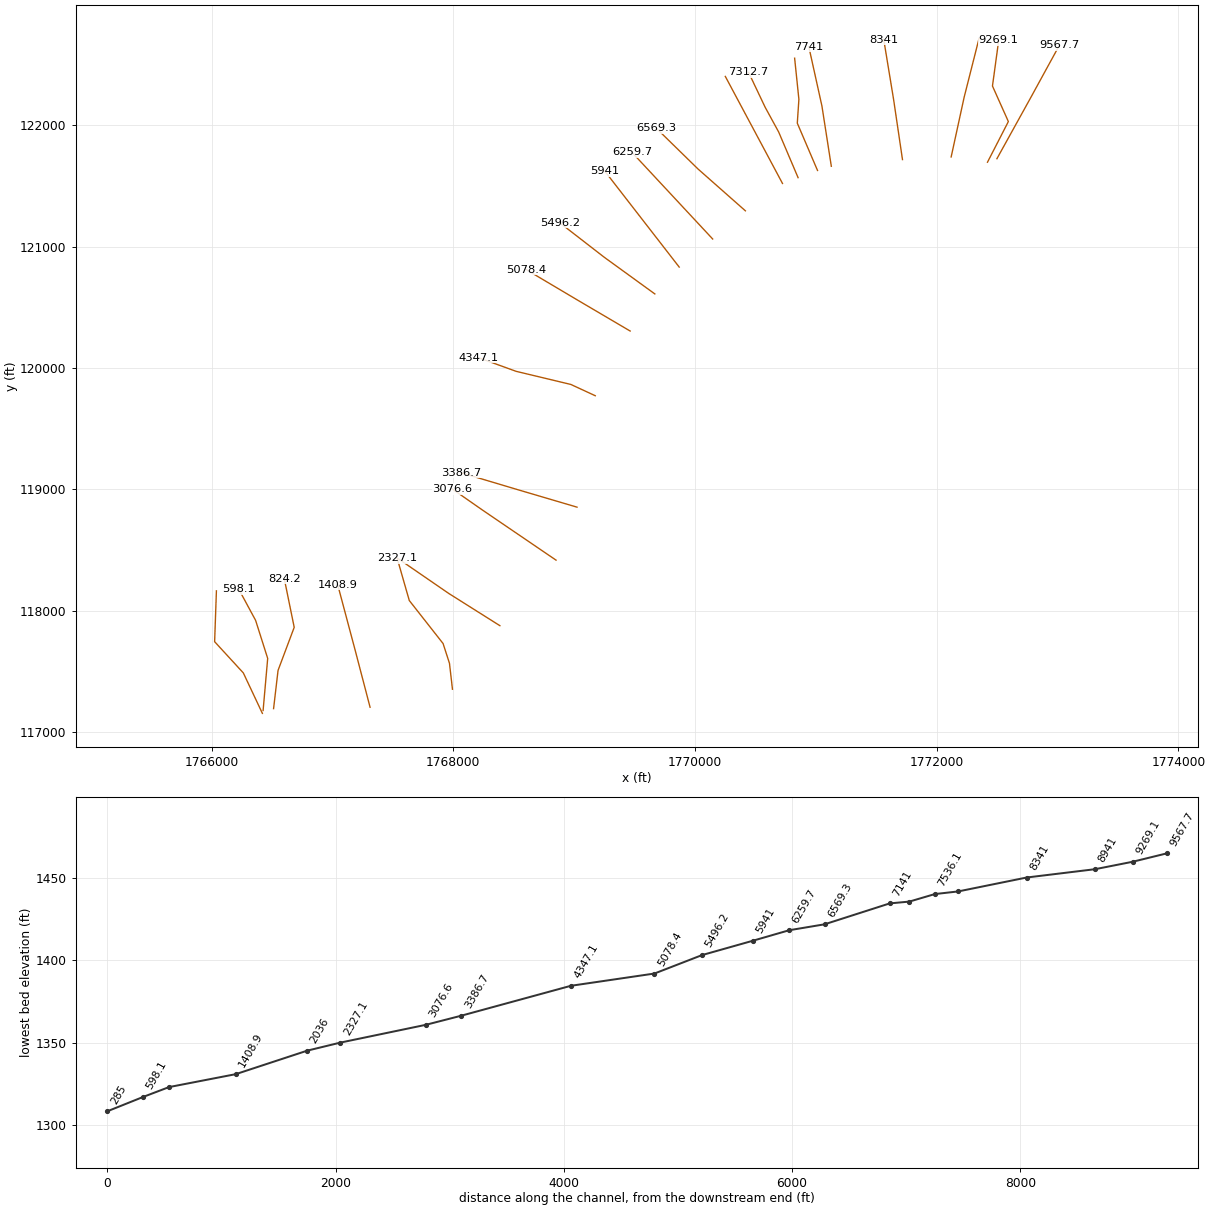
HEC-RAS study Barrenshe Creek.prj: Barrenshe Creek

--- Barrenshe Creek.g01 (geometry) --- (continued)

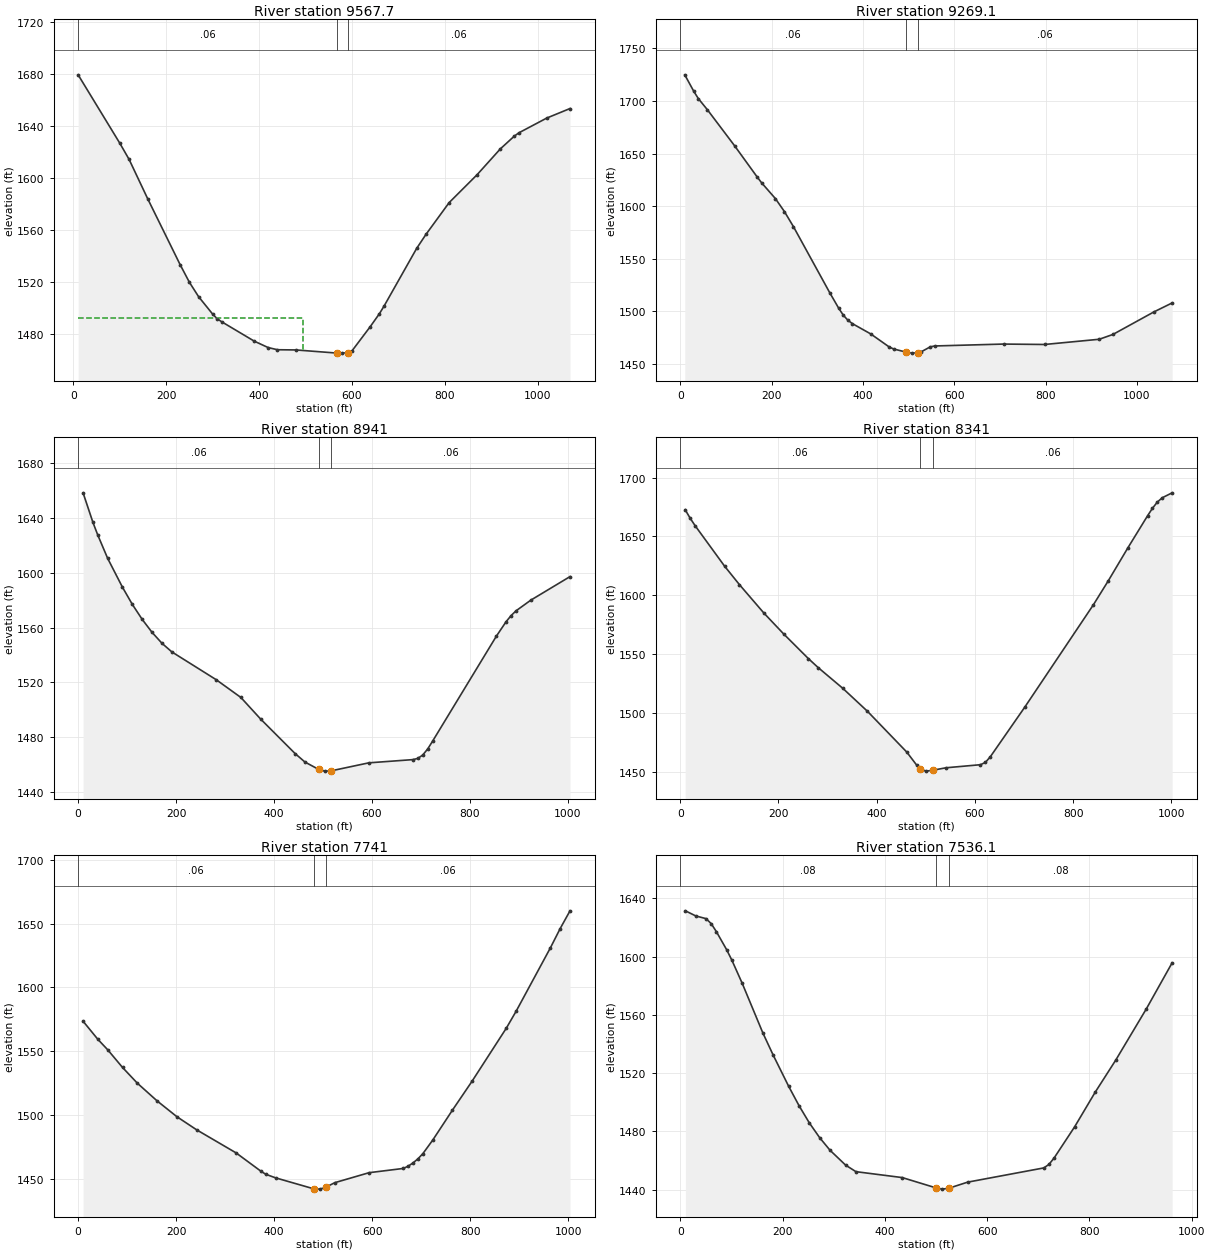
Type RM Length L Ch R = 1 ,9567.7  ,285.9,298.6,326.6
XS GIS Cut Line= 3
       1772498.5      121724.819     1772784.673      122239.802
     1773016.097      122660.898
#Sta/Elev= 30
      10 1679.17    99.9 1626.47   119.8 1614.08   159.8 1583.84   229.7 1533.12
   249.6 1519.59   269.6  1508.4   299.6 1495.13   309.6 1491.44   319.5 1489.09
   389.4 1474.22   419.4 1469.28   439.4 1467.61   479.3 1467.45   566.7 1465.06
   579.2    1465   591.7 1465.37   599.2 1466.36   639.2 1485.31   659.2  1495.4
   669.2 1501.27   739.3 1545.59   759.3 1556.34   809.4 1580.87   869.4 1602.25
   919.5 1622.14   949.5 1631.93   959.5 1634.54  1019.6  1645.9  1069.7 1653.23
#Mann= 3 , 0 , 0
      10     .06       0   566.7    .045       0   591.7     .06       0
#XS Ineff= 2 , 0
          493.82 1491.97
Permanent Ineff=
       F       F
Bank Sta=566.7,591.7
XS Rating Curve= 0 ,0
Exp/Cntr=0.3,0.1

Type RM Length L Ch R = 1 ,9269.1  ,346.3,328.1,308.9
XS GIS Cut Line= 4
     1772420.477      121696.034     1772593.209      122030.971
     1772461.638      122323.744      1772513.09      122699.341
#Sta/Elev= 30
     9.9 1724.92    29.8 1709.08    39.7 1702.24    59.5 1691.64     119 1657.36
   168.6 1627.52   178.5 1621.91   208.3 1607.09   228.1  1594.7   247.9 1580.29
   327.3 1517.44   347.1 1502.53     357 1496.05   366.9 1491.31   376.9    1488
     417 1478.22   457.1  1465.9   467.1 1463.87   494.8 1460.85   507.3 1459.92
   519.8 1460.25   527.3 1461.12   547.4 1465.91   557.4 1466.74   707.8 1468.55
   797.6 1468.15   917.3 1473.12   947.2 1477.69    1037 1499.16  1076.9 1507.71
#Mann= 3 , 0 , 0
       0     .06       0   494.8    .045       0   519.8     .06       0
Bank Sta=494.8,519.8
XS Rating Curve= 0 ,0
Exp/Cntr=0.3,0.1

Type RM Length L Ch R = 1 ,8941    ,589.9,600,611.5
XS GIS Cut Line= 3
     1772119.754      121739.271      1772227.25      122231.182
     1772350.722      122716.798
#Sta/Elev= 30
    10.1 1658.16    30.2 1636.64    40.3 1627.23    60.4 1610.35    90.6 1589.35
   110.8 1576.82   130.9 1565.93   151.1 1556.46   171.2 1548.56   191.3  1542.3
     282 1522.02   332.3 1509.11   372.6 1493.41   443.1 1468.23   463.2 1462.05
     491 1456.73   503.5 1455.42     516 1455.57   593.7 1461.46   683.9 1463.81
   693.9 1464.71   703.9 1467.19     714  1471.6     724 1477.28   854.3 1553.79
   874.3  1564.4   884.3 1568.73   894.4 1572.21   924.4 1579.94  1004.6 1597.13
#Mann= 3 , 0 , 0
       0     .06       0     491    .045       0     516     .06       0
Bank Sta=491,516
XS Rating Curve= 0 ,0
Exp/Cntr=0.3,0.1

Type RM Length L Ch R = 1 ,8341    ,599.8,600,601.5
XS GIS Cut Line= 3
      1771717.04      121717.701     1771643.411      122213.564
      1771561.93       122707.09
#Sta/Elev= 30
      10 1672.82    20.1 1665.62    30.1  1659.3    90.2  1624.8   120.3 1609.14
   170.4 1584.81   210.5 1567.12   260.7 1546.18   280.7  1538.5   330.9 1520.84
     381 1501.34   461.2 1466.58   481.2 1455.57   488.8 1452.53   491.3 1451.53
   501.3 1450.36   513.8  1451.1   541.3 1453.22   611.3 1455.83   621.3 1457.78
   631.4 1462.63   701.4 1504.76   841.4 1592.04   871.5  1612.3   911.5 1640.42
   951.5 1667.64   961.5 1674.04   971.5 1679.35   981.5 1682.99  1001.5 1687.16
#Mann= 3 , 0 , 0
       0     .06       0   488.8    .045       0   513.8     .06       0
Bank Sta=488.8,513.8
XS Rating Curve= 0 ,0
Exp/Cntr=0.3,0.1

Type RM Length L Ch R = 1 ,7741    ,211.3,205,196.8
XS GIS Cut Line= 3
     1771128.117      121662.502      1771050.25      122159.926
     1770941.806      122647.922
#Sta/Elev= 30
    10.1 1573.47    40.3 1559.26    60.4 1551.07    90.6 1537.23   120.8 1524.91
   161.1 1511.04   201.4 1498.67   241.7  1488.4   322.2 1470.31   372.6 1456.03
   382.6 1453.58   402.8 1450.75   480.9 1442.12   493.4 1441.91   505.9 1443.53
   523.5 1446.96   593.5 1454.79   663.4 1458.12   673.4 1459.93   683.4 1462.52
   693.4 1465.72   703.4 1469.79   723.4 1480.35   763.4 1503.71   803.4 1526.35
   873.4 1567.98   893.4 1581.24   963.4 1630.97   983.4 1646.11  1003.4 1659.97
#Mann= 3 , 0 , 0
       0     .06       0   480.9    .045       0   505.9     .06       0
Bank Sta=480.9,505.9
XS Rating Curve= 0 ,0
Exp/Cntr=0.3,0.1

Type RM Length L Ch R = 1 ,7536.1  ,207.5,223.4,239.3
XS GIS Cut Line= 4
     1771013.989      121627.907     1770846.595      122017.756
     1770859.811      122213.782      1770824.57      122552.973
#Sta/Elev= 30
    10.1 1631.37    30.3 1627.87    50.5    1626    60.6 1622.53    70.7 1617.05
    90.9 1604.56     101 1597.44   121.2 1581.57   161.6 1547.47   181.8 1532.26
   212.1 1510.82   232.3 1497.56   252.5 1485.72   272.7 1475.58   292.9 1466.98
   323.3  1456.8   343.5 1452.29   434.1 1448.23   500.2 1441.14   512.7  1440.3
   525.2 1440.92   561.8 1445.08     711 1454.87     721 1457.29   731.1 1461.71
   771.2  1483.1   811.3 1506.81   851.4 1528.79   911.6  1564.2   961.8 1595.67
#Mann= 3 , 0 , 0
       0     .08       0   500.2    .045       0   525.2     .08       0
Bank Sta=500.2,525.2
XS Rating Curve= 0 ,0
Exp/Cntr=0.3,0.1

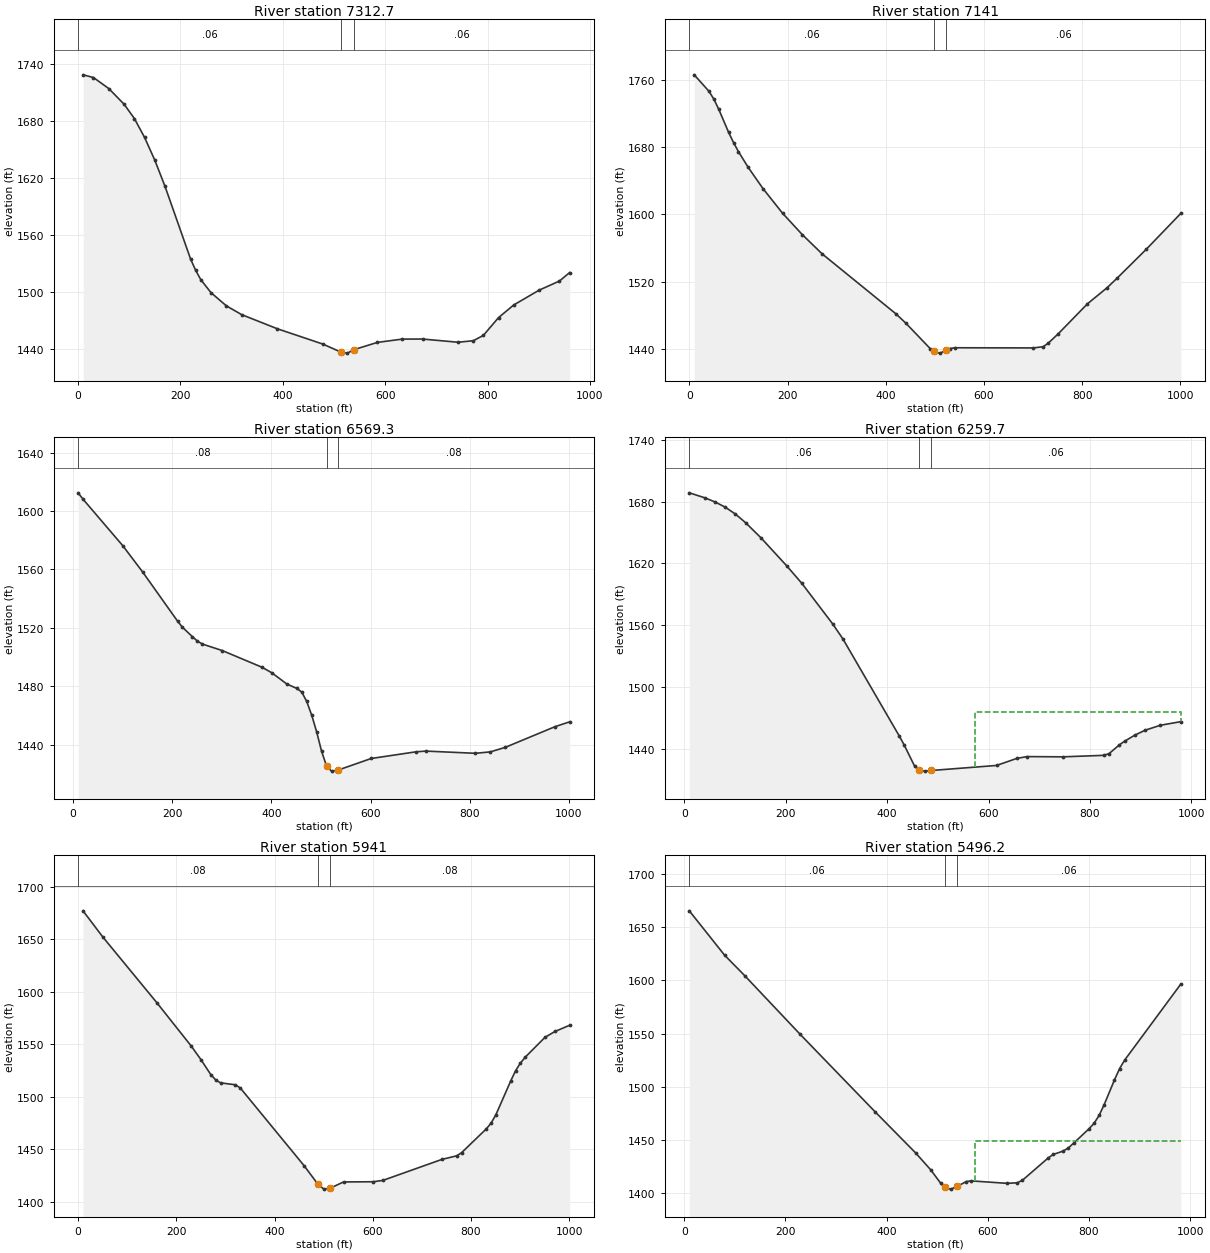
Type RM Length L Ch R = 1 ,7312.7  ,171.9,171.6,171.4
XS GIS Cut Line= 4
     1770853.203      121568.438     1770692.418      121945.072
     1770580.088      122149.909     1770443.531      122436.239
#Sta/Elev= 30
      10 1728.91      30 1726.04    59.9 1714.46    89.9  1697.9   109.9  1682.9
   129.8 1663.01   149.8 1639.05   169.8  1611.4   219.7 1534.93   229.7 1522.93
   239.7  1513.1   259.7 1499.42   289.7 1485.52   319.6 1476.28   389.5 1461.34
   477.7 1445.36   513.8 1436.73   526.3 1435.73   538.8 1439.36   584.7 1447.02
   633.4 1450.51   672.9 1450.58   742.3  1447.2     772 1448.78   791.8  1454.4
   821.6 1473.23   851.3  1486.5   900.9 1502.11   940.5 1511.68   960.4 1520.61
#Mann= 3 , 0 , 0
       0     .06       0   513.8    .045       0   538.8     .06       0
Bank Sta=513.8,538.8
XS Rating Curve= 0 ,0
Exp/Cntr=0.3,0.1

Type RM Length L Ch R = 1 ,7141    ,562.3,571.7,580.2
XS GIS Cut Line= 3
     1770724.139      121520.863     1770487.548      121961.913
     1770250.958      122402.963
#Sta/Elev= 30
      10 1766.44      40 1746.86      50 1737.45    60.1 1725.17    80.1 1697.75
    90.1 1685.65   100.1 1674.81   120.1 1655.97   150.2 1630.68   190.2 1601.24
   230.2 1575.87   270.3 1553.09   420.4 1481.66   440.4 1470.71   490.5 1440.08
     498 1436.63   500.5 1435.48   510.5 1434.64     523 1437.93   530.5 1440.09
   540.5 1441.04   700.7 1440.84   720.7 1442.29   730.7 1446.36   750.8 1457.38
   810.8 1493.43   850.8 1512.62   870.9 1523.83   930.9 1558.64    1001 1601.28
#Mann= 3 , 0 , 0
       0     .06       0     498    .045       0     523     .06       0
Bank Sta=498,523
XS Rating Curve= 0 ,0
Exp/Cntr=0.3,0.1

Type RM Length L Ch R = 1 ,6569.3  ,311.9,309.6,308.4
XS GIS Cut Line= 3
     1770417.219      121295.234     1770025.796      121639.379
      1769681.46      121974.395
#Sta/Elev= 30
      10  1612.4      20 1608.01   100.2 1576.17   140.3 1558.17   210.5 1524.64
   220.5 1520.38   240.6 1513.92   250.6 1510.95   260.6  1508.9   300.7 1504.46
   380.9 1493.04   400.9  1489.2     431 1481.57     451 1478.56   461.1 1476.08
   471.1 1469.66   481.1 1460.36   491.1 1448.94   501.2 1435.47   511.2 1425.42
   521.2 1421.93   533.7 1422.56   601.3 1430.58   691.3 1435.13   711.4 1435.65
   811.5 1434.13   841.5  1435.1   871.5 1438.17   971.6 1452.29  1001.6 1455.68
#Mann= 3 , 0 , 0
      10     .08       0   511.2    .045       0   533.7     .08       0
Bank Sta=511.2,533.7
XS Rating Curve= 0 ,0
Exp/Cntr=0.3,0.1

Type RM Length L Ch R = 1 ,6259.7  ,321.1,318.7,316.2
XS GIS Cut Line= 2
     1770146.314      121063.179     1769477.443      121778.357
#Sta/Elev= 30
    10.1 1688.53    40.4 1683.74    60.6 1679.73    80.8 1674.65     101 1667.93
   121.1 1659.54   151.4 1644.84   201.9 1617.79   232.2  1600.5   292.8 1561.25
   312.9 1546.73     424  1452.5   434.1 1443.37   454.3 1423.18     462 1419.64
   464.4 1418.53   474.5 1418.34     487 1418.95   615.8 1423.84   656.2 1430.75
   676.4 1432.45     747 1432.22   827.8 1433.67   837.9 1435.42   858.1 1443.89
   868.2 1447.35   888.4 1453.24   908.6 1458.02   938.8 1462.85   979.2 1466.38
#Mann= 3 , 0 , 0
    10.1     .06       0     462    .045       0     487     .06       0
#XS Ineff= 2 , 0
                          573.57         1476.06
Permanent Ineff=
       F       F
Bank Sta=462,487
XS Rating Curve= 0 ,0
Exp/Cntr=0.3,0.1

Type RM Length L Ch R = 1 ,5941    ,437,444.8,451.7
XS GIS Cut Line= 3
      1769869.28      120831.914     1769561.761      121226.796
     1769254.241      121621.679
#Sta/Elev= 30
      10 1677.03      50 1652.28   160.2  1589.6   230.2 1548.34   250.2 1535.28
   270.3 1520.97   280.3  1515.9   290.3 1513.14   320.3 1511.36   330.3 1508.28
   460.5 1434.11     488 1416.83   500.5 1411.95     513 1412.77   540.5  1418.8
   600.6 1418.97   620.6 1420.26   740.7 1440.24   770.8 1443.66   780.8  1446.6
   830.8 1469.14   840.8 1474.66   850.8  1482.8   880.9 1514.88   890.9 1524.73
   900.9 1532.16   910.9 1537.79   950.9 1556.59     971 1562.09    1001 1568.04
#Mann= 3 , 0 , 0
       0     .08       0     488    .045       0     513     .08       0
Bank Sta=488,513
XS Rating Curve= 0 ,0
Exp/Cntr=0.3,0.1

Type RM Length L Ch R = 1 ,5496.2  ,415.3,417.9,421.3
XS GIS Cut Line= 3
     1769667.814      120610.405     1769248.606      120913.049
     1768880.604      121196.953
#Sta/Elev= 30
     9.9 1665.69    79.5 1623.95   119.3 1604.64   228.7 1549.42   377.8 1475.92
   457.4 1437.42   487.2 1421.48   507.1  1408.7   514.6 1405.11     517 1403.96
   527.1 1403.25   539.6 1405.88   557.5 1410.37   567.6 1411.02   638.3  1408.7
   658.5 1409.24   668.6 1411.62   719.1 1432.48   729.2 1435.91   749.4 1439.19
   759.5 1442.17   769.6  1446.5     800 1460.05   810.1 1465.22   820.2 1472.74
   830.3 1483.02   850.5 1506.15   860.6  1516.8   870.7 1524.93   981.8 1596.64
#Mann= 3 , 0 , 0
     9.9     .06       0   514.6    .045       0   539.6     .06       0
#XS Ineff= 2 , 0
                           575.6         1448.46
Permanent Ineff=
       F       F
Bank Sta=514.6,539.6
XS Rating Curve= 0 ,0
Exp/Cntr=0.3,0.1

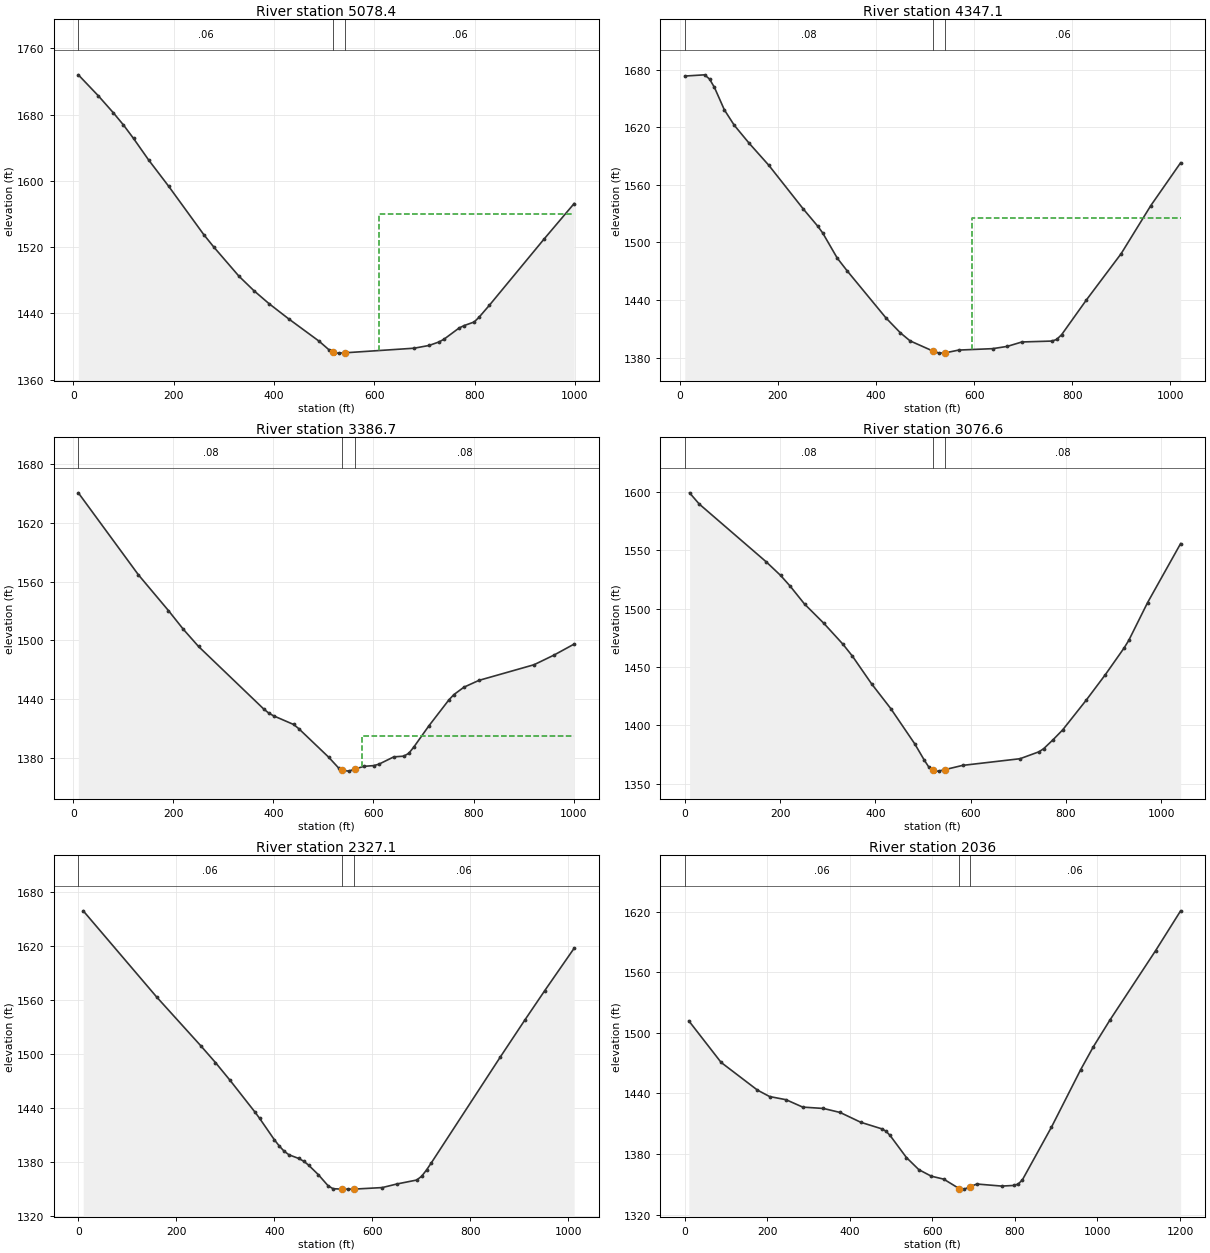
Type RM Length L Ch R = 1 ,5078.4  ,722.8,731.3,739.8
XS GIS Cut Line= 3
     1769463.455      120304.662     1769031.866       120557.51
     1768602.765      120811.066
#Sta/Elev= 30
      10 1727.89      50 1702.48      80 1681.96     100 1667.35     120 1651.16
   150.1  1625.2   190.1 1593.42   260.1 1535.07   280.1 1520.08   330.1 1484.97
   360.1 1467.39   390.2 1451.76   430.2 1433.03   490.2 1406.37   510.2 1395.81
   517.6 1393.35   520.1 1392.51   530.1 1392.03   542.6 1392.46   679.6 1397.97
   709.5 1401.32   729.5 1405.62   739.4 1408.96   769.3 1422.39   779.3 1425.31
   799.3 1429.62   809.2 1435.51   829.2 1449.53   938.8 1529.85   998.6 1572.59
#Mann= 3 , 0 , 0
      10     .06       0   517.6    .045       0   542.6     .06       0
#XS Ineff= 2 , 0
                          610.19         1559.59
Permanent Ineff=
       F       F
Bank Sta=517.6,542.6
XS Rating Curve= 0 ,0
Exp/Cntr=0.3,0.1

Type RM Length L Ch R = 1 ,4347.1  ,961.8,960.4,959
XS GIS Cut Line= 4
     1769174.724      119771.493     1768973.217      119864.356
     1768520.442      119972.404     1768206.587      120085.598
#Sta/Elev= 30
    10.1 1673.49    50.4 1674.77    60.5 1670.41    70.6 1661.57    90.8 1638.22
   110.9 1622.23   141.2  1603.5   181.5  1580.4   251.6 1534.93   281.3 1516.89
   291.2 1509.94   320.9  1483.7   340.7 1470.66     420 1421.45   449.7 1405.72
   469.5 1397.35   516.4 1386.68   528.9  1384.6   541.4 1384.91   568.5 1387.78
   637.8 1389.26   667.6 1391.63   697.5 1396.24   758.1 1397.17   768.2 1398.82
   778.4 1403.85   828.9 1440.06   899.7 1488.28   960.3 1538.51    1021 1583.09
#Mann= 3 , 0 , 0
    10.1     .08       0   516.4    .045       0   541.4     .06       0
#XS Ineff= 2 , 0
                          594.65         1525.65
Permanent Ineff=
       F       F
Bank Sta=516.4,541.4
XS Rating Curve= 0 ,0
Exp/Cntr=0.3,0.1

Type RM Length L Ch R = 1 ,3386.7  ,319,310.1,301.2
XS GIS Cut Line= 3
     1769023.744      118853.208     1768543.628      118994.262
      1768063.67      119136.704
#Sta/Elev= 30
      10  1650.6   130.1 1566.88   190.2 1530.33   220.2 1511.08   250.2 1493.76
   380.3 1430.02   390.3 1425.83   400.3  1422.9   440.4 1414.05   450.4 1409.92
   510.4 1380.67   530.4 1369.58     538 1367.32   550.5 1366.44     563 1368.56
   580.5 1371.31   600.5 1372.09   610.6 1373.48   640.6    1381   660.6 1381.73
   670.6 1384.67   680.6 1391.04   710.7 1412.67   750.7 1439.18   760.7 1444.58
   780.8 1452.16   810.8 1459.11     921 1475.09     961 1484.97  1001.1 1496.19
#Mann= 3 , 0 , 0
      10     .08       0     538    .045       0     563     .08       0
#XS Ineff= 2 , 0
                          576.27         1401.98
Permanent Ineff=
       F       F
Bank Sta=538,563
XS Rating Curve= 0 ,0
Exp/Cntr=0.3,0.1

Type RM Length L Ch R = 1 ,3076.6  ,749,749.5,749.7
XS GIS Cut Line= 3
     1768850.091      118416.621     1768242.962      118828.234
     1767990.849      119003.169
#Sta/Elev= 30
      10  1599.3    30.1 1589.77   170.8  1540.2     201 1528.56   221.1 1519.36
   251.2 1504.06   291.4 1487.69   331.6 1469.73   351.7 1459.42   391.9 1435.71
   432.1 1414.54   482.3 1384.42   502.4 1370.41   512.4 1364.15     520 1361.77
   522.5 1360.99   532.5 1360.91     545 1362.11   582.8 1365.82   703.4 1371.54
   743.4 1377.51   753.3 1380.23   773.1 1387.95   792.9 1396.24   842.4 1421.76
     882  1443.3   921.6 1466.29   931.5 1472.85   971.1  1505.3  1040.4 1555.83
#Mann= 3 , 0 , 0
       0     .08       0     520    .045       0     545     .08       0
Bank Sta=520,545
XS Rating Curve= 0 ,0
Exp/Cntr=0.3,0.1

Type RM Length L Ch R = 1 ,2327.1  ,300,291.1,282.5
XS GIS Cut Line= 3
     1768385.461      117876.522     1767962.126      118142.277
     1767539.615      118431.684
#Sta/Elev= 30
      10 1659.32   159.9 1563.56   249.9  1509.4   279.9 1490.73   309.9 1470.84
   359.9 1436.14   369.9 1428.83   399.9 1405.12   409.9 1398.18   419.9 1392.32
   429.9 1388.25   449.9 1384.17   459.9 1381.15   469.8 1376.85   489.8 1366.21
   509.9 1353.77   519.9 1350.56   537.5 1350.12     550  1350.1   562.5 1350.11
   620.3 1351.83   650.5 1355.85   690.6  1360.2   700.7 1364.41   710.7 1371.38
   720.8 1379.57   861.3 1496.93   911.5 1538.12   951.7 1570.44    1012 1617.79
#Mann= 3 , 0 , 0
       0     .06       0   537.5    .045       0   562.5     .06       0
Bank Sta=537.5,562.5
XS Rating Curve= 0 ,0
Exp/Cntr=0.3,0.1

Type RM Length L Ch R = 1 ,2036    ,638.3,627.1,616.1
XS GIS Cut Line= 5
     1767993.143      117352.489     1767968.416      117566.208
     1767915.555      117729.196     1767635.832      118083.805
     1767535.224      118432.973
#Sta/Elev= 30
     9.8 1511.95      88 1470.78     176 1443.36   205.4 1436.97   245.4 1433.82
   285.7  1426.5   336.1 1425.14   376.4 1421.17   426.6 1411.43   476.8 1405.02
   486.9 1402.82   496.9 1398.68     537 1376.54   567.2 1364.47   597.3 1358.03
   627.4  1355.1   665.1 1345.69   677.6  1345.2   690.1 1347.43   707.7 1350.27
   767.9 1348.22     798 1348.86     808 1350.29   818.1 1354.42   888.6  1406.7
   959.3  1463.6   989.6 1486.02  1029.9  1512.6    1141 1581.65  1201.5 1621.02
#Mann= 3 , 0 , 0
       0     .06       0   665.1    .045       0   690.1     .06       0
Bank Sta=665.1,690.1
XS Rating Curve= 0 ,0
Exp/Cntr=0.3,0.1

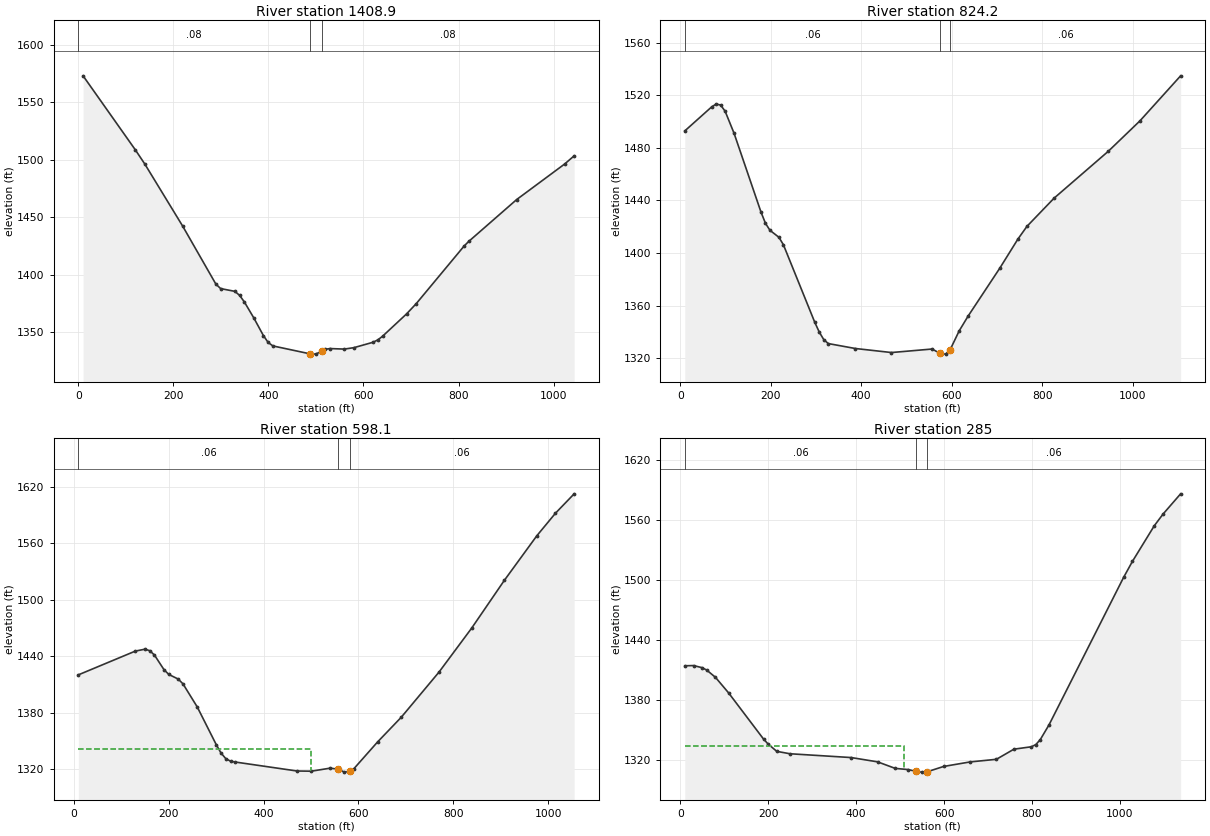
Type RM Length L Ch R = 1 ,1408.9  ,601.7,584.6,567.4
XS GIS Cut Line= 3
     1767311.329      117204.306     1767184.528      117687.156
      1767043.78      118212.758
#Sta/Elev= 30
      10 1573.11   119.8 1508.78   139.8  1496.4   219.7 1442.21   289.5 1391.79
   299.5 1387.95   329.5 1385.53   339.5 1381.98   349.5 1376.22   369.4 1362.29
   389.4 1347.07   399.4 1341.08   409.4 1338.05   486.7 1331.23   499.2 1330.91
   511.7 1333.27   519.4 1335.11   529.5 1335.75   559.7  1335.3   579.8 1336.53
   620.1 1341.23   630.2 1343.31   640.3 1346.54   690.7 1365.94   710.8 1374.75
   811.6 1424.91   821.7 1429.09   922.4 1465.46  1023.2 1496.34  1043.3 1503.48
#Mann= 3 , 0 , 0
       0     .08       0   486.7    .045       0   511.7     .08       0
Bank Sta=486.7,511.7
XS Rating Curve= 0 ,0
Exp/Cntr=0.3,0.1

Type RM Length L Ch R = 1 ,824.2   ,207.7,226.2,244.6
XS GIS Cut Line= 4
     1766512.889      117192.912     1766549.844       117507.87
     1766683.619      117862.887     1766601.296       118264.21
#Sta/Elev= 30
     9.9 1492.89    69.4  1511.2    79.3 1513.33    89.2 1512.55    99.1 1507.84
   118.9 1491.03   178.4 1431.11   188.3 1422.56   198.2 1417.27     218 1411.95
   227.9  1406.3   297.3 1347.26   307.2 1339.85   317.1 1334.14   327.1  1331.1
     387 1327.34   466.9 1324.27   556.7 1326.94   574.2 1323.65   586.7 1323.06
   596.7 1326.49   616.6 1340.78   636.6 1352.15   706.5 1388.52   746.5 1410.63
   766.4 1420.26   826.4 1441.72   946.3  1477.4  1016.3 1500.55  1106.2  1534.8
#Mann= 3 , 0 , 0
     9.9     .06       0   574.2    .045       0   596.7     .06       0
Bank Sta=574.2,596.7
XS Rating Curve= 0 ,0
Exp/Cntr=0.3,0.1

Type RM Length L Ch R = 1 ,598.1   ,300.6,313.1,325.5
XS GIS Cut Line= 4
     1766426.206      117177.664     1766464.126      117606.753
     1766364.151      117920.213     1766223.823      118179.038
#Sta/Elev= 30
      10 1420.26   130.2  1445.5   150.3 1447.48   160.3 1445.92   170.3 1441.29
   190.3 1425.85   200.4 1420.74   220.4 1415.79   230.4 1410.72   260.5 1386.16
   300.5  1346.2   310.5 1337.34   320.6 1331.37   330.6 1328.69   340.6 1327.79
   470.6 1318.28   500.6 1318.08   540.4 1321.31   557.8 1320.15   570.3 1317.09
   582.8 1318.03   590.3 1320.71   640.1 1349.05     690 1375.25   769.6 1423.21
   838.3  1469.8     907 1520.38   975.7 1567.87  1014.9 1591.77  1054.2 1612.29
#Mann= 3 , 0 , 0
      10     .06       0   557.8    .045       0   582.8     .06       0
#XS Ineff= 2 , 0
          499.43 1341.91
Permanent Ineff=
       F       F
Bank Sta=557.8,582.8
XS Rating Curve= 0 ,0
Exp/Cntr=0.3,0.1

Type RM Length L Ch R = 1 ,285     ,272.5,285,297.5
XS GIS Cut Line= 4
     1766420.219      117153.715     1766262.554      117487.007
     1766025.058      117744.461     1766039.839      118163.447
#Sta/Elev= 30
      10  1414.4    29.9 1414.63    49.8 1412.47    59.8 1410.15    79.7 1402.93
   109.6 1387.42   189.3 1341.28   199.3 1336.54   219.2 1329.12   249.1 1326.72
   388.7 1322.92   448.8 1318.63   488.8 1312.13   518.8 1310.92   536.3 1309.11
   548.8  1308.4   561.3 1308.73   598.9 1314.05   658.9 1318.55     719 1321.18
   758.9 1331.28   798.8 1333.69   808.8  1335.9   818.8 1340.77   838.8 1355.55
  1008.4 1502.47  1028.4 1518.38  1078.3 1554.01  1098.3 1565.68  1138.2 1585.82
#Mann= 3 , 0 , 0
      10     .06       0   536.3    .045       0   561.3     .06       0
#XS Ineff= 2 , 0
          508.13  1334.2
Permanent Ineff=
       F       F
Bank Sta=536.3,561.3
XS Rating Curve= 0 ,0
Exp/Cntr=0.3,0.1

Chan Stop Cuts=-1
Use User Specified Reach Order=0